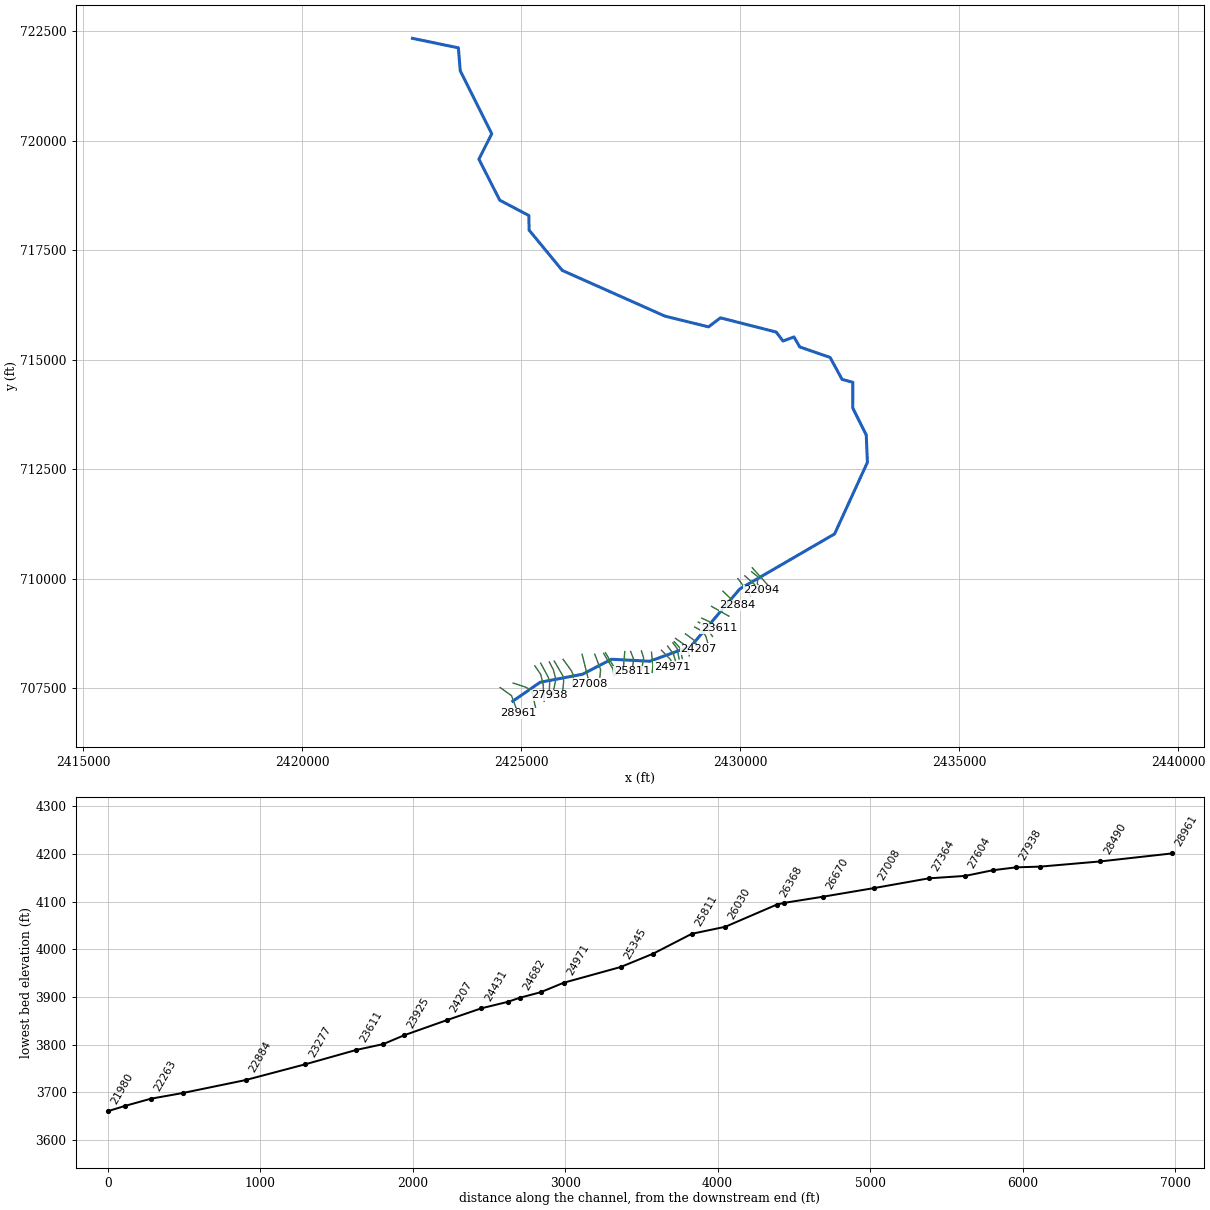
--- SFKREDCK.prj (project) ---

Proj Title=SFKREDCK
Current Plan=p01
Default Exp/Contr=0,0
English Units
Geom File=g01
Flow File=f01
Plan File=p01
BEGIN DESCRIPTION:
----------MODEL BY WOOD PLC 2022----------
AFH study
Randolph County, WV
HEC-RAS Version: RAS 6.2
Vertical Datum: NAVD88
Projection: NAD 1983 StatePlane West Virginia S FIPS 4702 (US Feet)
Terrain: 1-meter LIDAR (FEMA Region III 3DEP collected 2016-2018)
Land Use: 2019 NLCD
Hydrologic Method:
WV SIR2010-5033 regression equations
Additional Model Notes:
None
END DESCRIPTION:
DSS Export Rating Curves= 0
DSS Export Rating Curve Sorted= 0
DSS Export Volume Flow Curves= 0
DXF OffsetX= 0
DXF OffsetY= 0
DXF ScaleX= 0
DXF ScaleY= 0

--- SFKREDCK.p01 (plan) ---

Plan Title=Floodplain
Program Version=6.20
Short Identifier=Floodplain
Geom File=g01
Flow File=f01
Subcritical Flow
K Sum by GR= 0
Std Step Tol= 0.01
Critical Tol= 0.01
Num of Std Step Trials= 20
Max Error Tol= 0.3
Flow Tol Ratio= 0.001
Split Flow NTrial= 30
Split Flow Tol= 0.02
Split Flow Ratio= 0.02
Log Output Level= 0
Friction Slope Method= 1
Unsteady Friction Slope Method= 2
Unsteady Bridges Friction Slope Method= 1
Parabolic Critical Depth
Global Vel Dist= 0 , 0 , 0
Global Log Level= 0
CheckData=True
Encroach Param=-1 ,0,0, 0
Mapping Interval=1HOUR
Computation Time Step Use Courant=        0
Computation Time Step Use Time Series=    0
Computation Time Step Count To Double=0
Computation Time Step Max Doubling=0
Computation Time Step Max Halving=0
Computation Time Step Residence Courant=0
Run HTab= 0
Run UNet= 0
Run Sediment= 0
Run PostProcess= 0
Run WQNet= 0
Run RASMapper=-1
UNET Theta= 0
UNET Theta Warmup= 0
UNET ZTol= 0
UNET ZSATol= 0
UNET MxIter= 0
UNET Max Iter WO Improvement= 0
UNET MaxInSteps= 0
UNET DtIC= 0
UNET DtMin= 0
UNET MaxCRTS= 0
UNET WFStab= 0
UNET SFStab= 0
UNET WFX= 1
UNET SFX= 1
UNET Gravity=32.174
UNET 1D Methodology=Finite Difference
UNET DSS MLevel= 1
UNET Pardiso=0
UNET DZMax Abort= 0
UNET Use Existing IB Tables= 0
UNET Froude Reduction=False
UNET Froude Limit= 0
UNET Froude Power= 0
UNET D1 Cores= 0
UNET WindReference=Eulerian
UNET WindDragFormulation=Hsu (1988)
UNET D2 Coriolis=0
UNET D2 Cores= 0
UNET D2 Theta= 1
UNET D2 Theta Warmup= 1
UNET D2 Z Tol= 0.01
UNET D2 Volume Tol= 0.01
UNET D2 Max Iterations= 20
UNET D2 Equation= 0
UNET D2 RampUpFraction=0.1
UNET D2 TimeSlices= 1
UNET D2 Turbulence Formulation=Non-Conservative (original)
UNET D2 Eddy Viscosity=0.3
UNET D2 Transverse Eddy Viscosity=0.1
UNET D2 Smagorinsky Mixing=0
UNET D2 BCVolumeCheck=0
UNET D2 Cores=0
UNET D2 SolverType=PARDISO (Direct)
UNET D2 Minimum Iterations= 2147483647
UNET D2 Maximum Iterations= 2147483647
UNET D2 Restart Number= 10
UNET D2 Relaxation Coeff=1.3
UNET D2 SOR Precondition Iterations= 10
UNET D2 ILUT Maximum Fill= 8
UNET D2 ILUT Tolerance=1E-08
UNET D1D2 MaxIter= 0
UNET D1D2 ZTol=0.01
UNET D1D2 QTol=0.1
UNET D1D2 MinQTol=1
Write IC File= 0
Write IC File at Fixed DateTime=0
Write IC File at Sim End=0
Echo Input=False
Echo Parameters=False
Echo Output=False
Write Detailed= 0
HDF Write Warmup=0
HDF Write Time Slices=0
HDF Flush=0
HDF Compression= 1
HDF Chunk Size= 1
HDF Spatial Parts= 1
HDF Use Max Rows=0
HDF Fixed Rows= 1
Calibration Method= 0
Calibration Iterations= 20
Calibration Max Change=0.05
Calibration Tolerance=0.2
Calibration Maximum=1.5
Calibration Minimum=0.5
Calibration Optimization Method= 1
WQ AD Non Conservative
WQ ULTIMATE=-1
WQ Max Comp Step=1HOUR
WQ Output Interval=15MIN
WQ Output Selected Increments= 0
WQ Output face flow=0
WQ Output face velocity=0
WQ Output face area=0
WQ Output face dispersion=0
WQ Output cell volume=0
WQ Output cell surface area=0
WQ Output cell continuity=0
WQ Output cumulative cell continuity=0
WQ Output face conc=0
WQ Output face dconc_dx=0
WQ Output face courant=0
WQ Output face peclet=0
WQ Output face adv mass=0
WQ Output face disp mass=0
WQ Output cell mass=0
WQ Output cell source sink temp=0
WQ Output nsm pathways=0
WQ Output nsm derived pathways=0
WQ Create Restart=0
WQ Fixed Restart=0
WQ System Summary=0
WQ Write To DSS=0
Sorting and Armoring Iterations= 10
XS Update Threshold= 0.02
Bed Roughness Predictor= 0
Hydraulics Update Threshold= 0.02
Energy Slope Method= 1
Volume Change Method= 1
Sediment Retention Method= 0
Sediment TS Multiplier= 1
Warm Up Method= 0
XS Weighting Method= 0
Number of US Weighted Cross Sections= 1
Number of DS Weighted Cross Sections= 1
Upstream XS Weight=0
Main XS Weight=1
Downstream XS Weight=0
Number of DS XS's Weighted with US Boundary= 1
Upstream Boundary Weight= 1
Weight of XSs Associated with US Boundary= 0
Number of US XS's Weighted with DS Boundary= 1
Downstream Boundary Weight= 0.5
Weight of XSs Associated with DS Boundary= 0.5
Percentile Method= 0
Sediment Output Level= 3
Mass or Volume Output= 0
Output Increment Type= 1
Profile and TS Output Increment= 1
Transport Output Increment 1
XS Output Flag= 0
XS Output Increment= 10
Read HDF5 Sediment Hotstart= 0
Sediment Hotstart Type= 0
Write Gradation File= 0
Read Gradation Hotstart= 0
Write HDF5 File= 1
Write Binary Output= 1
Write DSS Sediment File= 0
DSS Sediment Output Type= 1
SV Curve= 0
Specific Gage Flag= 0
Subcell Erosion Methods= 0
Subcell Deposition Methods= 0
Advection Scheme= 1
Matrix Solver= 0
Implicit Weighting Factor= 1
Maximum Outer Loop Convergence Iterations= 5
Convergence Maximum Absolute= 0.001
Convergence RMSE= 0.0001
Grain Fractions Max Abs Error= 0.001
Max Subgrid Regions= 1
Max Subgrid Length Scale= 3.402823E+38
Initial Layer Thickness= 3.402823E+38
Min Layer Thickness= 3.402823E+38
Max Layer Thickness= 3.402823E+38
Number of Layers= 5

--- SFKREDCK.f01 (steady flow) ---

Flow Title=Flow
Program Version=6.20
Number of Profiles= 1
Profile Names=P100yr
River Rch & RM=SFKREDCK,Main,28961
     435
River Rch & RM=SFKREDCK,Main,26030
     484
River Rch & RM=SFKREDCK,Main,25345
     548
River Rch & RM=SFKREDCK,Main,23787
     618
River Rch & RM=SFKREDCK,Main,22263
     687
River Rch & RM=SFKREDCK,Main,19612
     802
River Rch & RM=SFKREDCK,Main,17792
     914
River Rch & RM=SFKREDCK,Main,14263
    1040
River Rch & RM=SFKREDCK,Main,13148
    1180
River Rch & RM=SFKREDCK,Main,10808
    1350
River Rch & RM=SFKREDCK,Main,7083
    1740
Boundary for River Rch & Prof#=SFKREDCK,Main            , 1
Up Type= 0
Dn Type= 3
Dn Slope=0.03104
DSS Import GetInterval= 0
DSS Import GetPeak= 0
DSS Import FillOption= 0

--- SFKREDCK.g01 (geometry) ---

Geom Title=Geometry
Program Version=6.20

River Reach=SFKREDCK        ,Main
Reach XY= 30
2424807.38892807707205.6142087052425432.45299998      707636.875
2426398.59900005707820.0349999962427060.92500004708162.481999993
2427935.75499998 708116.760000022428874.41300002      708458.412
2429990.26700002709766.1239999982432156.07199998711023.078999996
2432905.32760987712656.959085209     2432878.575713281.944000006
2432569.71199998713897.6510000082432572.91211578714483.056512341
     2432325.823714549.8910000322432053.39536811715051.130280152
2431360.24536811715289.5267882942431229.01700002715518.623999998
2430976.80796058715425.2186523532430821.49700002715630.606000021
 2429548.3620144715954.7602122712429278.05839017715748.609650257
2428283.18888672715992.8156610732425937.61364859717036.551320763
2425179.34299998717957.4430000342425175.07700001718288.757000014
     2424509.928718639.5450000022424033.59400003719575.085999995
2424326.52000003720155.1870000062423607.74500002 721594.21100001
2423564.92687257722116.507957533 2422517.5185205722333.568116456

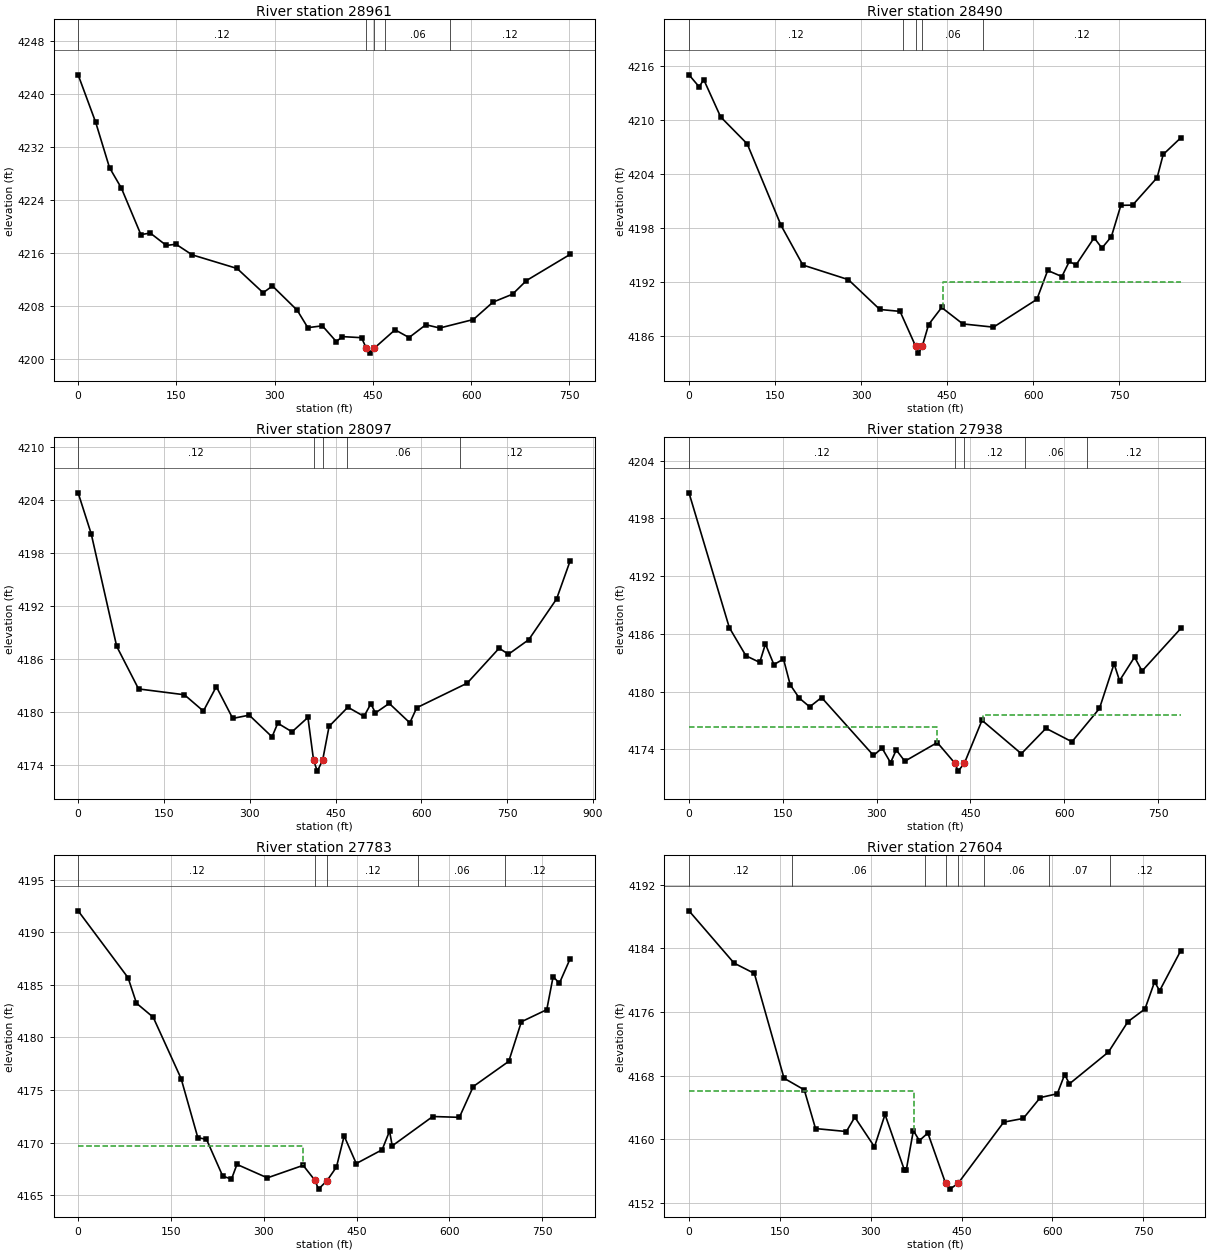
Type RM Length L Ch R = 1 ,28961   ,466.8,471.2,475.3
XS GIS Cut Line= 3
2424518.41905518707516.9613076862424777.58355351707332.521038471
2424929.05830434  706927.0225368
#Sta/Elev= 30
       0  4242.9    26.9 4235.71    47.9  4228.9      66 4225.82    95.8  4218.8
   110.2 4219.03   134.7 4217.16   149.4 4217.35     174 4215.75   242.7 4213.69
   282.5 4210.03   296.7 4211.05   334.5 4207.39   350.7 4204.76   372.9 4205.04
   394.2 4202.66   403.5 4203.41   432.7 4203.25  439.99 4201.67   445.5 4200.92
  452.194201.669   483.9 4204.44   505.3 4203.27   530.9  4205.2   552.2 4204.71
   603.5 4205.99   633.4 4208.61   663.3 4209.81   684.6 4211.87     751  4215.8
#Mann= 5 ,-1,0
       0     .12       0  439.99    .045       0  452.19     .12       0
   468.1     .06       0   568.1     .12       0
Bank Sta=439.99,452.19
XS Rating Curve= 0 ,0
Exp/Cntr=0.3,0.1

Type RM Length L Ch R = 1 ,28490   ,396.2,393.5,384
XS GIS Cut Line= 4
2424815.76871129707619.1303313782425093.45935836707528.124830669
2425235.56797789707452.5719898422425327.94029952 707059.30398212
#Sta/Elev= 30
       0    4215    17.7 4213.67    25.7 4214.47    55.1 4210.34   101.5 4207.34
   160.4 4198.31   198.4 4193.91   277.7 4192.29   332.6 4188.98   367.8 4188.77
  394.784184.932   399.9 4184.14  406.674184.931   417.6 4187.31   440.3  4189.2
   477.2 4187.38   530.6 4187.02   606.2  4190.1   625.1 4193.31   649.8 4192.63
   662.8 4194.31   674.4 4193.91     706 4196.93   719.6 4195.79   736.1 4197.06
   752.6 4200.53     773 4200.55   815.8  4203.6   826.4 4206.17   857.1 4208.02
#Mann= 5 ,-1,0
       0     .12       0  372.22     .06       0  394.78    .045       0
  406.67     .06       0  513.17     .12       0
#XS Ineff= 2 , 0
                          442.28         4191.99
Permanent Ineff=
       F       F
Bank Sta=394.78,406.67
XS Rating Curve= 0 ,0
Exp/Cntr=0.3,0.1

Type RM Length L Ch R = 1 ,28097   ,158.2,158.5,159.1
XS GIS Cut Line= 4
2425310.39880924708011.960849223 2425446.8871321707815.012190221
2425500.33762875 707583.756980242425524.12946657707201.837494402
#Sta/Elev= 30
       0 4204.77    22.9 4200.12    67.4 4187.38   105.6 4182.56   185.7  4181.9
   218.9 4180.05   241.5 4182.82   270.2 4179.22     299 4179.59   338.9 4177.13
   348.9 4178.68   373.8  4177.7   401.6 4179.33  411.524174.473     418 4173.25
   427.34174.473   438.6 4178.32   471.4 4180.49   499.6 4179.45   511.6 4180.88
   519.6 4179.84   543.7 4180.92   579.7 4178.72   591.8 4180.43   679.9 4183.21
   735.8 4187.17   752.1 4186.49   787.6 4188.14   836.2 4192.75   859.6 4197.01
#Mann= 5 ,-1,0
       0     .12       0  411.52    .045       0   427.3     .12       0
  469.62     .06       0  666.97     .12       0
Bank Sta=411.52,427.3
XS Rating Curve= 0 ,0
Exp/Cntr=0.3,0.1

Type RM Length L Ch R = 1 ,27938   ,155,154.7,154.3
XS GIS Cut Line= 4
2425444.21028125708072.5898626772425619.23771313 707749.56260249
2425649.78085407707644.843262122 2425636.0915525707335.191683234
#Sta/Elev= 30
       0 4200.66    64.5 4186.65      91 4183.73   113.1 4183.04   122.2 4184.95
   135.8 4182.81   151.1 4183.39   161.8 4180.72   176.2 4179.34     193 4178.42
     212 4179.39     295 4173.37   308.7 4174.13   322.3 4172.62   331.4 4173.94
   345.1 4172.77     397 4174.71  425.18 4172.56   430.3 4171.74   440.34172.555
   468.5 4177.02   531.4 4173.55   570.8 4176.19   612.3 4174.79   656.3 4178.25
   679.7  4182.9   688.4 4181.14   712.4 4183.59   724.4 4182.14   786.4 4186.57
#Mann= 5 ,-1,0
       0     .12       0  425.18    .045       0   440.3     .12       0
  536.48     .06       0  636.48     .12       0
#XS Ineff= 2 , 0
          396.75 4176.31  469.54         4177.53
Permanent Ineff=
       F       F
Bank Sta=425.18,440.3
XS Rating Curve= 0 ,0
Exp/Cntr(USF)=0,0
Exp/Cntr=0.3,0.1

Type RM Length L Ch R = 1 ,27783   ,181.4,179.7,179.1
XS GIS Cut Line= 4
2425640.97452676708100.8586085692425733.77449165707921.913183514
2425791.58829415707701.566238155 2425714.4429004707344.496753409
#Sta/Elev= 30
       0 4192.03    80.7 4185.67    94.3 4183.25   121.3 4181.92   166.4 4176.09
   193.4 4170.48   207.4 4170.32   233.6 4166.83   247.8 4166.54   256.6 4167.94
   305.7 4166.66   363.6 4167.85  382.68 4166.42   388.4 4165.59  402.23  4166.4
   417.4 4167.69   429.8 4170.64   449.4 4168.02   491.2 4169.33   503.2 4171.11
   507.5  4169.7     573 4172.49     616 4172.41   638.5 4175.34   695.8 4177.73
   716.2 4181.49   757.2 4182.64   767.5 4185.78   777.6 4185.15   794.7 4187.44
#Mann= 5 ,-1,0
       0     .12       0  382.68    .045       0  402.23     .12       0
  549.38     .06       0  689.38     .12       0
#XS Ineff= 2 , 0
          362.93 4169.68
Permanent Ineff=
       F       F
Bank Sta=382.68,402.23
XS Rating Curve= 0 ,0
Exp/Cntr(USF)=0,0
Exp/Cntr=0.3,0.1

Type RM Length L Ch R = 1 ,27604   ,236.2,239.3,243.4
XS GIS Cut Line= 4
2425753.67925481708121.4193079852425954.12143701707779.014916969
2425969.39300748707662.2964855162425940.18099973707366.317196822
#Sta/Elev= 30
       0  4188.7    74.4 4182.14   107.9 4180.84   156.9 4167.69   190.3 4166.23
   208.9 4161.37   259.8    4161   273.7  4162.8   306.2 4159.08   323.6 4163.14
   355.7 4156.14   358.7 4156.18   370.4 4161.11   380.3 4159.86   394.3 4160.81
  423.55 4154.51   430.9 4153.77  444.374154.511   519.6 4162.18   551.8 4162.64
   579.9 4165.26     608 4165.74   620.1 4168.14   628.1 4166.99   692.5 4170.98
   724.6 4174.79   752.7 4176.38   768.6 4179.79   776.9 4178.67   811.9 4183.72
#Mann= 8 ,-1,0
       0     .12       0     170     .06       0     390     .12       0
  423.55    .045       0  444.37     .12       0  486.76     .06       0
  594.47     .07       0  694.47     .12       0
#XS Ineff= 2 , 0
          370.73 4166.07
Permanent Ineff=
       F       F
Bank Sta=423.55,444.37
XS Rating Curve= 0 ,0
Exp/Cntr=0.3,0.1

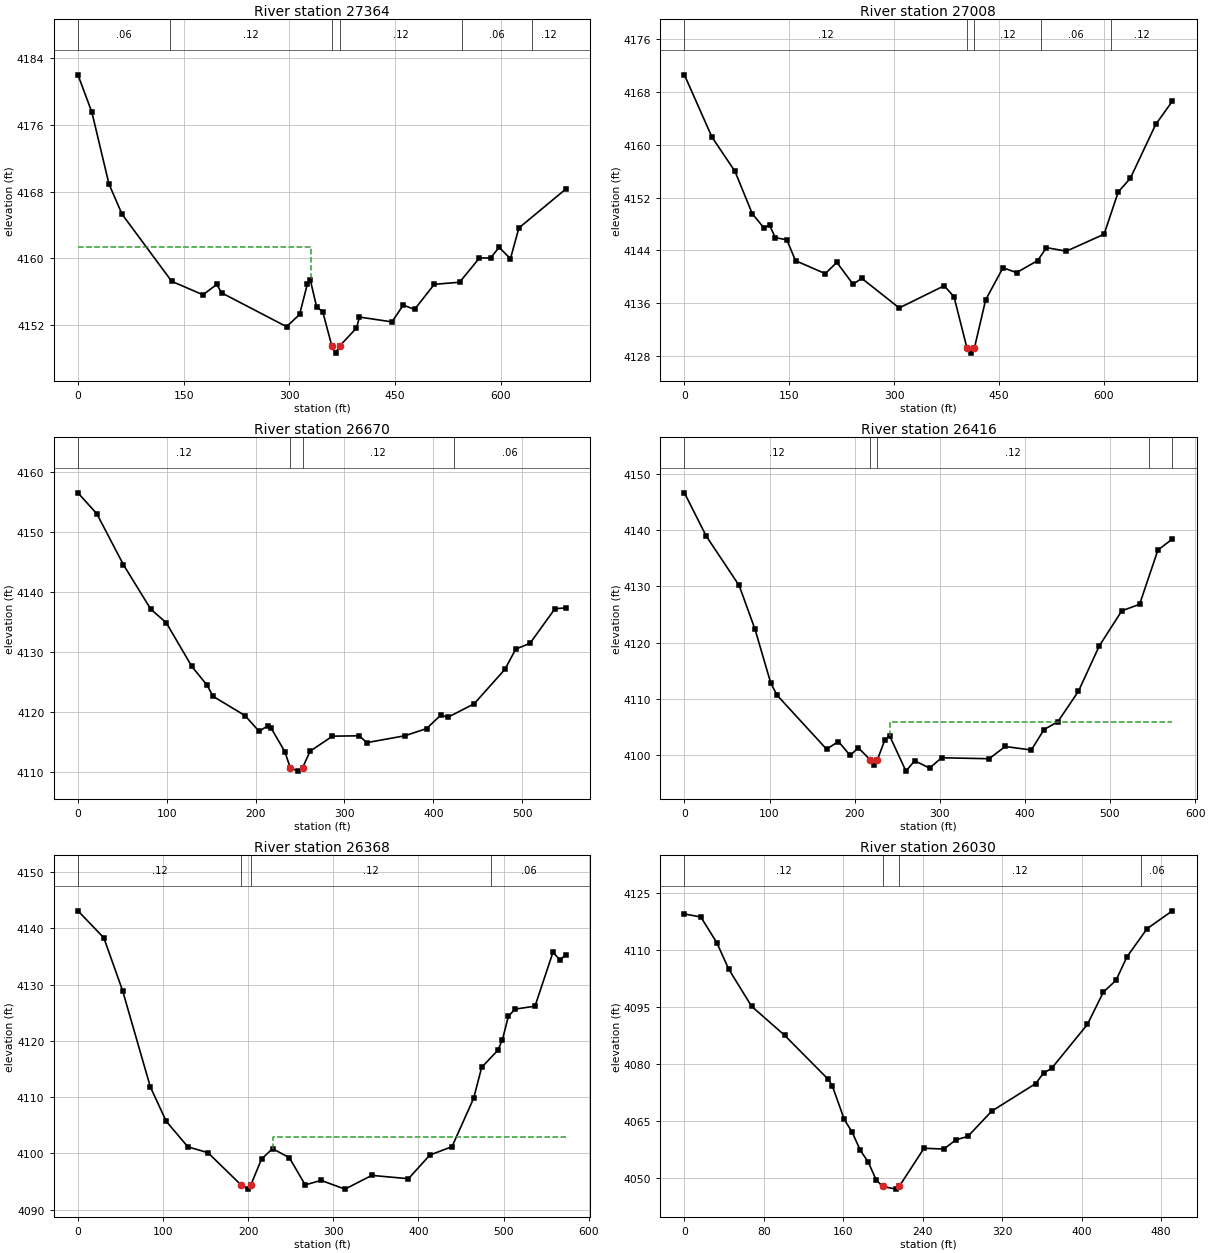
Type RM Length L Ch R = 1 ,27364   ,355.6,356.4,353.9
XS GIS Cut Line= 4
2425956.56949902708160.8399279912426147.19772082707897.915001346
2426186.46747346707806.2855785242426177.69362105707538.473193279
#Sta/Elev= 30
       0 4181.98    19.8 4177.49      44 4168.91    62.5  4165.3     133 4157.25
   177.4 4155.64   197.1 4156.88   203.8 4155.87     296 4151.82   314.5 4153.28
   325.6 4156.95   329.9 4157.35   338.6 4154.21   347.4 4153.59  360.354149.484
   365.7 4148.65  371.154149.484   395.2 4151.65   399.5 4152.97   445.6 4152.39
   461.6 4154.41   477.6 4153.88   505.6 4156.89   541.6 4157.14   569.6 4160.04
   585.6 4160.05   597.6 4161.32   613.7 4159.96   625.7 4163.64   692.4 4168.31
#Mann= 6 ,-1,0
       0     .06       0     130     .12       0  360.35    .045       0
  371.15     .12       0  544.45     .06       0  644.45     .12       0
#XS Ineff= 2 , 0
          330.08 4161.37
Permanent Ineff=
       F       F
Bank Sta=360.35,371.15
XS Rating Curve= 0 ,0
Exp/Cntr(USF)=0,0
Exp/Cntr=0.3,0.1

Type RM Length L Ch R = 1 ,27008   ,336.9,338.4,337.5
XS GIS Cut Line= 2
2426389.76008668708275.3658554592426559.58514892707598.031535399
#Sta/Elev= 30
       0 4170.63    39.4 4161.18    72.4 4155.97    97.1 4149.54   113.6 4147.41
   121.8 4147.79   130.1 4145.91   146.6 4145.57     159 4142.41   201.6 4140.44
   218.1 4142.15   241.4 4138.83   253.8 4139.73   307.4 4135.23   371.8  4138.6
   385.8 4136.93  404.334129.149   410.5 4128.37  415.034129.149   431.1 4136.47
   455.9 4141.33   475.3  4140.6   505.4 4142.41   518.1 4144.39   546.6 4143.85
   600.6 4146.43   620.8 4152.84   638.1 4154.91   674.4 4163.09   698.3 4166.63
#Mann= 5 ,-1,0
       0     .12       0  404.33    .045       0  415.03     .12       0
     510     .06       0     610     .12       0
Bank Sta=404.33,415.03
XS Rating Curve= 0 ,0
Exp/Cntr(USF)=0,0
Exp/Cntr=0.3,0.1

Type RM Length L Ch R = 1 ,26670   ,253.4,254.1,253.6
XS GIS Cut Line= 3
2426679.79509258708277.0545178832426812.32298772707928.116144695
2426795.89429659707752.953126571
#Sta/Elev= 30
       0 4156.58    21.3 4153.07    51.2 4144.57    81.9 4137.16    99.4 4134.88
   128.2 4127.58   145.3 4124.46   152.1 4122.59   188.1 4119.37   203.9 4116.75
   213.8 4117.69   217.3 4117.32   232.8 4113.37  238.964110.651   247.5  4110.1
  252.794110.649   261.3 4113.43   286.5 4115.94   316.5    4116   325.1 4114.86
   367.8    4116   392.3  4117.2   408.3 4119.44   416.4  4119.1   445.9 4121.34
   480.7 4127.13   492.7 4130.47   508.8 4131.45   536.9 4137.23   549.2 4137.36
#Mann= 4 ,-1,0
       0     .12       0  238.96    .045       0  252.79     .12       0
  423.26     .06       0
Bank Sta=238.96,252.79
XS Rating Curve= 0 ,0
Exp/Cntr=0.3,0.1

Type RM Length L Ch R = 1 ,26416   ,47.6,47.4,46.6
XS GIS Cut Line= 3
2426880.17807971708296.3425624062427094.13314441707939.750787907
2427119.53420232707784.413549152
#Sta/Elev= 30
       0 4146.58    25.6 4138.92    64.3 4130.14      83 4122.35   101.4 4112.85
   108.8 4110.68     167  4101.1     181 4102.45   194.7 4099.98   204.3 4101.34
  218.124099.238   222.9 4098.33  226.75 4099.22   235.5 4102.74     241  4103.5
   260.3  4097.2   270.5 4099.04     288 4097.74   302.2 4099.57     358  4099.4
   376.9 4101.57   407.6 4100.95   422.5 4104.58   438.7 4105.95     463 4111.39
   487.4 4119.41   513.9 4125.65   534.8  4126.8   556.3 4136.43   573.3 4138.39
#Mann= 5 ,-1,0
       0     .12       0  218.12    .045       0  226.75     .12       0
  545.85     .06       0  573.25     .12       0
#XS Ineff= 2 , 0
                             241            4106
Permanent Ineff=
       F       F
Bank Sta=218.12,226.75
XS Rating Curve= 0 ,0
Exp/Cntr(USF)=0,0
Exp/Cntr=0.3,0.1

Type RM Length L Ch R = 1 ,26368   ,340.2,337.7,332.9
XS GIS Cut Line= 3
 2426923.4874311708310.155972528 2427137.4424958707953.564198029
2427162.84355371707798.226959274
#Sta/Elev= 30
       0  4143.1    30.4 4138.31    52.5  4128.9    85.1 4111.79   103.8 4105.69
   129.1 4101.17   152.8 4100.12  191.624094.398   199.5 4093.66  203.24 4094.43
   215.7 4098.99   228.6 4100.85   248.4 4099.23     267  4094.4   285.7  4095.2
   313.7 4093.65   345.2 4096.09   388.3  4095.5   413.4  4099.7   439.5  4101.2
   464.9 4109.79   474.3 4115.28   493.3 4118.32   498.7 4120.19   505.7 4124.36
   513.5 4125.63     537 4126.16   558.1 4135.74   566.2  4134.4   573.3 4135.28
#Mann= 4 ,-1,0
       0     .12       0  191.62    .045       0  203.24     .12       0
  485.85     .06       0
#XS Ineff= 2 , 0
                           228.6            4103
Permanent Ineff=
       F       F
Bank Sta=191.62,203.24
XS Rating Curve= 0 ,0
Exp/Cntr(USF)=0,0
Exp/Cntr=0.3,0.1

Type RM Length L Ch R = 1 ,26030   ,220,219.9,218.8
XS GIS Cut Line= 2
2427364.74891246 708337.623207992427324.16018502707847.898315008
#Sta/Elev= 30
       0 4119.38    16.5  4118.6    32.6 4111.86    44.6 4104.91    67.7 4095.14
   100.8 4087.56   144.9 4075.96     149 4074.23     161 4065.43     169 4062.07
     177  4057.4   185.1 4054.26   193.1  4049.6  199.494047.853   213.2 4047.15
  216.334047.855   241.3 4057.88   261.3 4057.67   273.4 4060.09   285.4 4060.98
   309.5 4067.63   353.7 4074.85   361.7 4077.64   369.7 4078.83   405.8 4090.38
   421.9 4098.88   434.6 4101.95   445.7 4108.15     466 4115.54   491.4 4120.21
#Mann= 4 ,-1,0
       0     .12       0  199.49    .045       0  216.33     .12       0
     460     .06       0
Bank Sta=199.49,216.33
XS Rating Curve= 0 ,0
Exp/Cntr=0.3,0.1

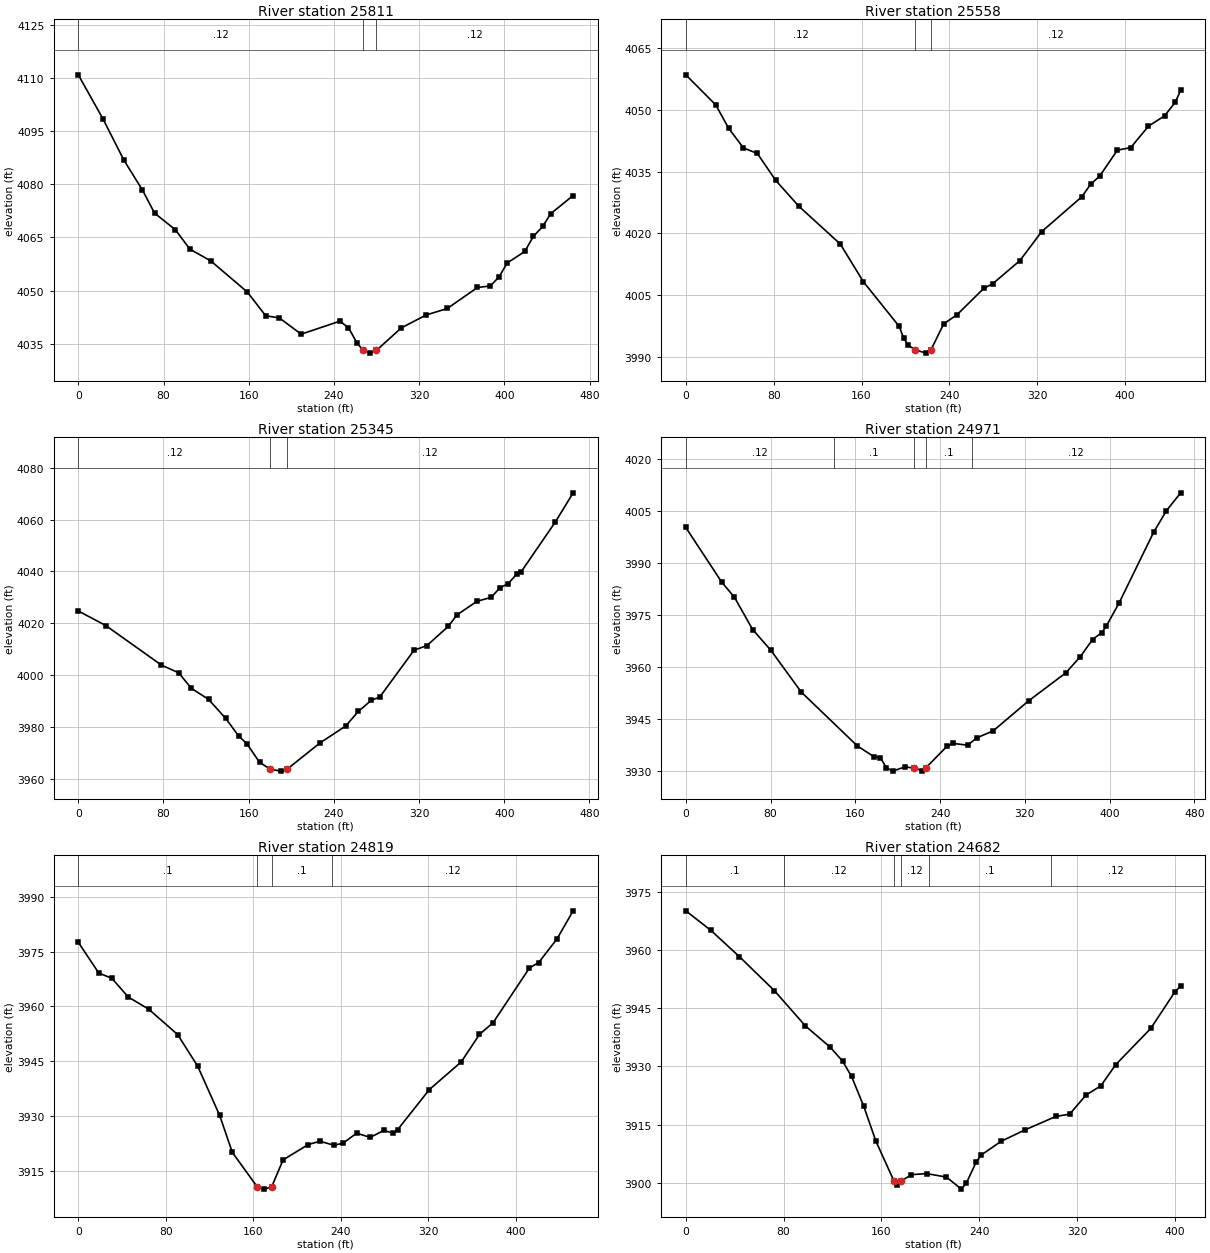
Type RM Length L Ch R = 1 ,25811   ,251.3,252.8,249.7
XS GIS Cut Line= 3
2427498.26250244708341.1657341472427568.04261896708161.286776175
2427531.55901361707892.186510302
#Sta/Elev= 30
       0 4110.84    23.1 4098.47    42.9 4086.75    60.1 4078.44    71.6 4071.87
    91.1 4067.18   104.8  4061.7   124.4 4058.39   158.7 4049.61   175.9 4042.95
   188.8 4042.32   209.2 4037.75   245.5 4041.41   253.6 4039.59   261.7  4035.2
  267.514033.168   273.8 4032.41   279.84033.168   303.1  4039.5   326.3 4043.13
   346.4 4044.99   374.7 4050.92   386.8 4051.34   394.9 4053.88   402.6  4057.8
   419.1 4061.06   427.2 4065.33     436 4068.12   443.3 4071.67   464.5 4076.83
#Mann= 3 ,-1,0
       0     .12       0  267.51    .045       0   279.8     .12       0
Bank Sta=267.51,279.8
XS Rating Curve= 0 ,0
Exp/Cntr=0.3,0.1

Type RM Length L Ch R = 1 ,25558   ,210.2,212.9,214.1
XS GIS Cut Line= 3
2427745.16389157708351.1890281582427795.23282618708195.091761421
2427748.10912301707912.349542426
#Sta/Elev= 30
       0 4058.55    27.3 4051.22      39 4045.55    52.5 4040.76    65.1 4039.43
    81.9 4032.86   102.9 4026.59   140.7 4017.38   161.7 4008.21   194.3 3997.35
   198.3 3994.55   202.4 3992.79  209.033991.651   218.6 3990.85  223.263991.649
   234.8 3997.96     247  4000.2   271.3  4006.6   279.5 4007.74   304.2 4013.35
     324  4020.4   360.5 4028.86   368.6 4031.92   376.7 4033.87     393 4040.23
   405.1 4040.84   421.3 4046.07   435.9 4048.56   445.7 4051.88   450.6 4054.82
#Mann= 3 ,-1,0
       0     .12       0  209.03    .045       0  223.26     .12       0
Bank Sta=209.03,223.26
XS Rating Curve= 0 ,0
Exp/Cntr(USF)=0,0
Exp/Cntr=0.3,0.1

Type RM Length L Ch R = 1 ,25345   ,368.4,374,376.6
XS GIS Cut Line= 3
2427974.64349499708322.8704124672428005.99987738708014.104620951
 2427989.3010446707860.672037918
#Sta/Elev= 30
       0  4024.7    25.8 4019.08    78.1  4003.8    94.2 4000.85   106.2 3994.85
   122.3 3990.58   138.4 3983.26   150.5 3976.49   158.5 3973.36   170.2 3966.29
  180.473963.556   190.7 3962.88  195.853963.557   226.9 3973.73     251 3980.27
     263 3985.92   275.1 3990.22   283.1 3991.47   315.3 4009.55   327.4 4011.34
   347.5 4018.77   355.5 4023.16   374.5 4028.46   387.7 4029.94   395.8 4033.58
   403.8  4035.3   411.9 4039.02   415.9 4039.83   448.1 4059.12   464.7  4070.3
#Mann= 3 ,-1,0
       0     .12       0  180.47    .045       0  195.85     .12       0
Bank Sta=180.47,195.85
XS Rating Curve= 0 ,0
Exp/Cntr=0.3,0.1

Type RM Length L Ch R = 1 ,24971   ,152.1,151.8,150.4
XS GIS Cut Line= 3
2428200.20669552708369.3145867462428414.79108794708148.583959111
2428444.13794745707992.054444073
#Sta/Elev= 30
       0 4000.31      34 3984.47    45.9 3980.15    63.1  3970.8    80.3 3964.81
     109 3952.73     162 3937.14   177.8 3934.02   183.6 3933.81   189.3 3930.86
   195.3 3929.88   206.6 3931.09   215.1 3930.81   223.3 3929.99   226.4 3930.77
   246.7 3937.12   252.4 3937.89     266 3937.38   274.5 3939.46   290.3 3941.56
   323.5 3950.18   358.8 3958.32   372.4 3962.98   383.9 3967.92   392.7 3969.95
   396.8 3971.74     409 3978.51   441.5 3998.89   453.7 4005.18   467.1 4010.33
#Mann= 5 ,-1,0
       0     .12       0     140      .1       0   215.1    .045       0
   226.4      .1       0     270     .12       0
Bank Sta=215.1,226.4
XS Rating Curve= 0 ,0
Exp/Cntr=0.3,0.1

Type RM Length L Ch R = 1 ,24819   ,138.6,137,135.4
XS GIS Cut Line= 3
2428342.58101466708461.7542856392428476.09217321708284.022641642
2428539.22258196708062.805341557
#Sta/Elev= 30
       0 3977.59    18.7 3969.16    30.7 3967.71    45.7 3962.58    64.4 3959.24
    90.8  3952.3   109.2 3943.58   129.2 3930.15   140.8    3920  163.443910.618
   170.1 3909.94  176.823910.617   187.2 3917.95   210.1 3922.15   220.8 3923.06
   233.6 3921.98   241.9  3922.5   254.4 3925.27   266.8 3924.12   279.3 3926.03
   287.6 3925.28   291.8  3926.2   320.9 3937.23     350 3944.79   366.7 3952.34
   379.2 3955.57   412.4 3970.56   420.8 3972.03   437.4 3978.44   452.3  3986.2
#Mann= 4 ,-1,0
       0      .1       0  163.44    .045       0  176.82      .1       0
  232.29     .12       0
Bank Sta=163.44,176.82
XS Rating Curve= 0 ,0
Exp/Cntr(USF)=0,0
Exp/Cntr=0.3,0.1

Type RM Length L Ch R = 1 ,24682   ,77.6,77,79.9
XS GIS Cut Line= 3
2428463.35402648708537.6837142752428558.42645105708410.727244885
2428605.55909446708169.114509555
#Sta/Elev= 30
       0 3970.17    20.6  3965.1    43.8 3958.35    72.4 3949.59    97.9 3940.44
   118.1 3934.98   128.2  3931.4   135.6 3927.41   145.6 3919.69   155.5 3910.72
   170.33900.413   172.4 3899.41   176.2 3900.43   184.6 3902.07   196.9 3902.35
   213.2 3901.45   225.4 3898.34   229.5 3899.91   237.6 3905.36   241.7 3907.16
     258 3910.69   277.4 3913.62   302.8 3917.11     314 3917.69   327.3  3922.6
   339.5    3925   351.7 3930.48   380.3  3939.8   400.1 3949.26   404.8 3950.74
#Mann= 6 ,-1,0
       0      .1       0      80     .12       0   170.3    .045       0
   176.2     .12       0  198.61      .1       0  298.61     .12       0
Bank Sta=170.3,176.2
XS Rating Curve= 0 ,0
Exp/Cntr(USF)=0,0
Exp/Cntr=0.3,0.1

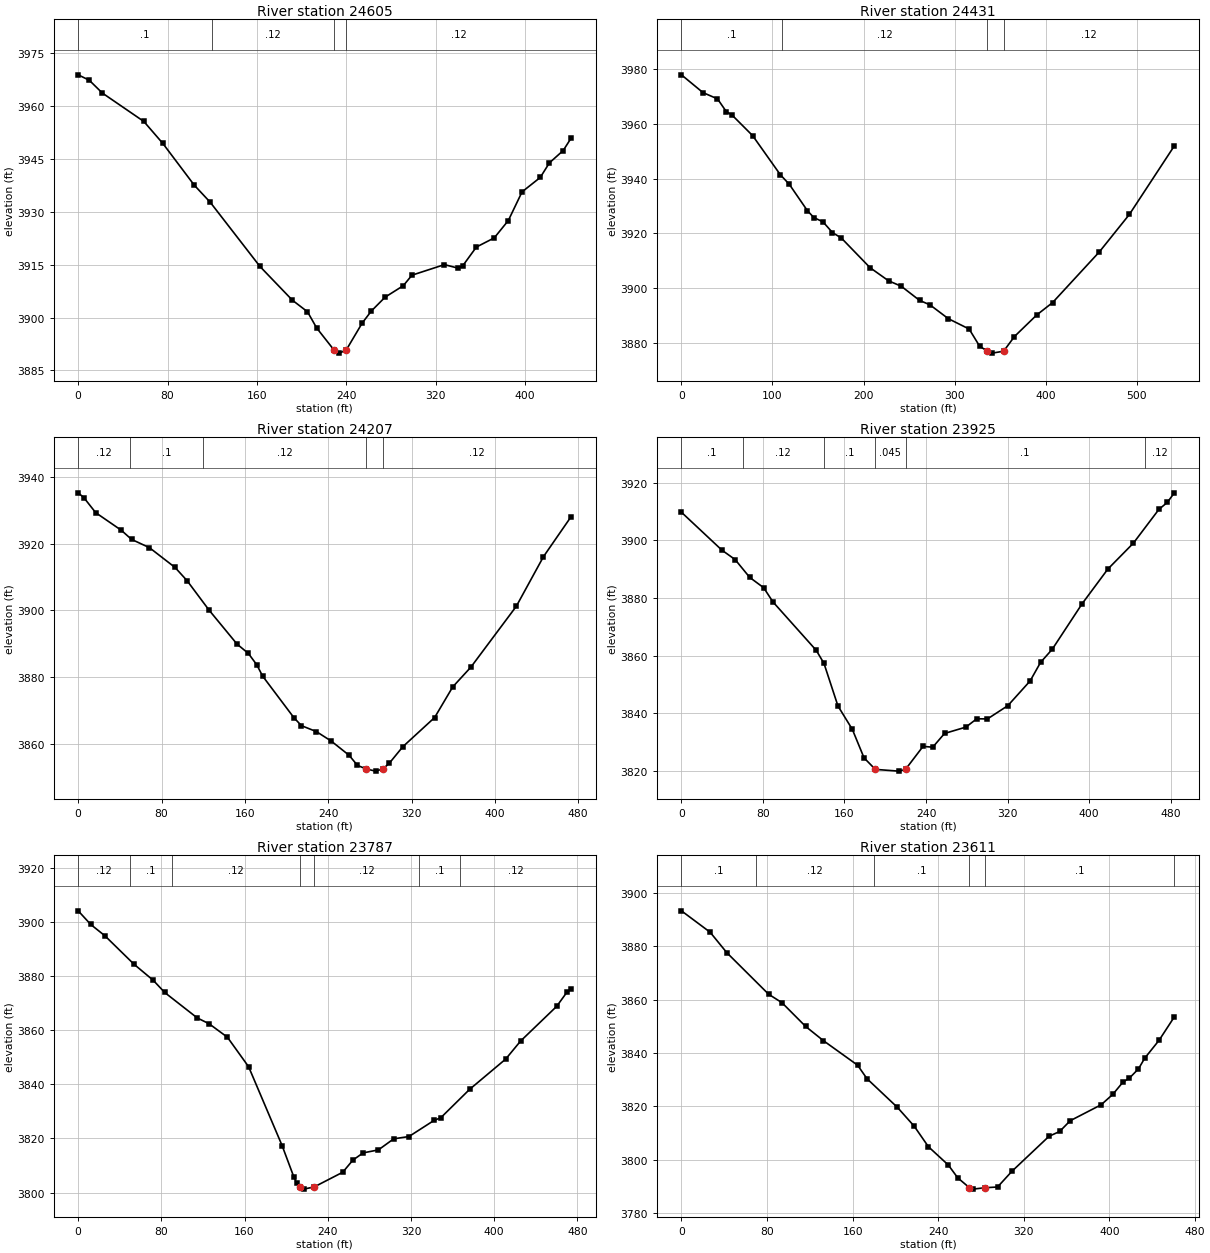
Type RM Length L Ch R = 1 ,24605   ,173.7,174,173.8
XS GIS Cut Line= 3
2428493.44746592708561.5384816562428627.83837688708416.809808308
2428677.93676381708178.246061031
#Sta/Elev= 30
       0 3968.83     9.9  3967.3    21.6 3963.67    58.8  3955.6    75.8 3949.37
   103.9 3937.55   118.2  3932.7   162.7  3914.5   191.8 3904.91   205.3 3901.64
   213.5 3897.05  229.033890.797   233.9 3889.91  239.993890.798   254.3 3898.45
   262.5 3901.86   274.8 3905.78   291.1 3909.04   298.8 3912.01   327.9 3915.01
   340.2    3914   344.3 3914.68   356.5 3919.99   372.5 3922.59   385.1 3927.51
   397.4 3935.64   413.7 3939.73   421.9 3943.87   434.2 3947.35   441.3 3950.87
#Mann= 4 ,-1,0
       0      .1       0     120     .12       0  229.03    .045       0
  239.99     .12       0
Bank Sta=229.03,239.99
XS Rating Curve= 0 ,0
Exp/Cntr(USF)=0,0
Exp/Cntr=0.3,0.1

Type RM Length L Ch R = 1 ,24431   ,222.9,224.5,226
XS GIS Cut Line= 3
2428524.07166287708638.2109550432428798.24756956708440.520362102
2428835.66826677708240.633070278
#Sta/Elev= 30
       0  3977.8    23.7 3971.31    39.6 3969.04    49.4 3964.33    55.3 3963.23
    78.2 3955.63   108.6 3941.39   118.5 3937.87   138.3  3928.3   145.4 3925.76
   155.5 3924.19   165.9 3920.28   175.6 3918.31   207.2 3907.48   227.5  3902.7
   241.5 3900.71   261.5 3895.57     273 3893.93   293.1  3888.9     316 3885.12
   327.5 3878.88  336.043877.036   341.4 3876.33   353.93877.038   365.8 3882.39
   390.2 3890.23   407.7 3894.77   459.1 3913.27     492 3926.89   541.4  3951.9
#Mann= 4 ,-1,0
       0      .1       0     110     .12       0  336.04    .045       0
   353.9     .12       0
Bank Sta=336.04,353.9
XS Rating Curve= 0 ,0
Exp/Cntr=0.3,0.1

Type RM Length L Ch R = 1 ,24207   ,280.3,281.5,282.1
XS GIS Cut Line= 3
2428749.08480675708741.6301173252428960.10898015708587.269842337
2429044.12786401708392.854052952
#Sta/Elev= 30
       0 3935.27     5.4 3933.84    16.8 3929.32    41.4 3924.03    51.2  3921.3
    68.4 3918.81      93 3912.87   104.5 3908.92   125.6 3900.08   152.5 3889.87
   163.4 3887.06   171.4 3883.68   177.1 3880.25     207 3867.82   214.3 3865.39
   228.7  3863.6     243 3860.75   260.1 3856.49   268.1 3853.47  276.353852.409
   285.5 3851.74  292.523852.408   298.6 3854.08   311.7 3859.08   342.2 3867.83
   359.6 3877.03     377 3882.95   420.6 3901.21   446.7 3916.12   473.2 3928.11
#Mann= 5 ,-1,0
       0     .12       0      50      .1       0     120     .12       0
  276.35    .045       0  292.52     .12       0
Bank Sta=276.35,292.52
XS Rating Curve= 0 ,0
Exp/Cntr(USF)=0,0
Exp/Cntr=0.3,0.1

Type RM Length L Ch R = 1 ,23925   ,135.2,138.1,137.8
XS GIS Cut Line= 4
2428961.30304204708897.7456146672429109.65679906708816.935031574
2429210.97155996708698.7344771992429258.01055609 708546.76233586
#Sta/Elev= 30
       0  3909.7    39.7 3896.56    52.7 3893.28      67  3887.1    80.7 3883.52
    89.8  3878.6   132.3 3861.79   139.9 3857.25   153.6 3842.48   167.7 3834.38
   179.2 3824.49  190.263820.498   213.1 3819.89  219.893820.498   237.1 3828.48
   246.6 3828.19   258.2 3832.96   279.2 3835.17   289.8 3838.05   300.3    3838
   320.3  3842.6   342.2 3851.19   352.4  3857.6   363.9 3862.18   393.2 3877.96
   418.4 3889.97   443.5 3898.98   468.6 3910.72   476.8 3913.11   483.7 3916.44
#Mann= 6 ,-1,0
       0      .1       0      60     .12       0     140      .1       0
  190.26    .045       0  219.89      .1       0  454.61     .12       0
Bank Sta=190.26,219.89
XS Rating Curve= 0 ,0
Exp/Cntr(USF)=0,0
Exp/Cntr=0.3,0.1

Type RM Length L Ch R = 1 ,23787   ,172.2,176.1,177.2
XS GIS Cut Line= 3
2429042.11358581709011.7716081052429203.14411522708915.868981699
2429368.46879209708681.837945621
#Sta/Elev= 30
       0 3904.26    12.1  3899.2    25.7 3895.02    53.6 3884.52    72.2 3878.54
    83.2 3874.04   114.5 3864.62   125.9 3862.46   143.5 3857.48   163.9 3846.55
   196.1 3817.37   207.3 3805.85   210.2 3803.43  213.173802.076   216.9 3801.26
  226.983802.075   254.4 3807.51   264.2 3812.01     274 3814.67   288.7 3815.78
   303.4 3819.87   318.1 3820.73   342.2 3826.69   348.7 3827.68   376.4 3838.18
   411.1 3849.39   425.4 3856.05   460.1 3868.89   469.9 3874.09     474 3875.42
#Mann= 7 ,-1,0
       0     .12       0      50      .1       0      90     .12       0
  213.17    .045       0  226.98     .12       0  327.43      .1       0
  367.43     .12       0
Bank Sta=213.17,226.98
XS Rating Curve= 0 ,0
Exp/Cntr(USF)=0,0
Exp/Cntr=0.3,0.1

Type RM Length L Ch R = 1 ,23611   ,331.7,333.5,333.7
XS GIS Cut Line= 3
2429123.11327113709100.5334056022429341.50530105708998.370684143
2429518.65703232708868.845642698
#Sta/Elev= 30
       0 3893.19    26.8 3885.19    42.4 3877.54    81.5 3861.98    93.9 3858.84
     116 3849.96   132.7 3844.61   164.6 3835.45   173.4 3830.39   201.9 3819.63
   217.6 3812.58   230.8 3804.94   249.4  3798.1   258.2  3793.3   269.1 3789.62
   272.5 3789.08   283.8 3789.61   295.4 3789.87   308.8 3795.74   343.5 3808.85
   353.4 3810.64   363.3 3814.67   392.2 3820.64     403 3824.49   412.7 3829.16
   418.5 3830.57   427.1 3834.08   432.9 3838.05   446.4  3844.8   460.6 3853.52
#Mann= 6 ,-1,0
       0      .1       0      70     .12       0     180      .1       0
   269.1    .045       0   283.8      .1       0  460.56     .12       0
Bank Sta=269.1,283.8
XS Rating Curve= 0 ,0
Exp/Cntr=0.3,0.1

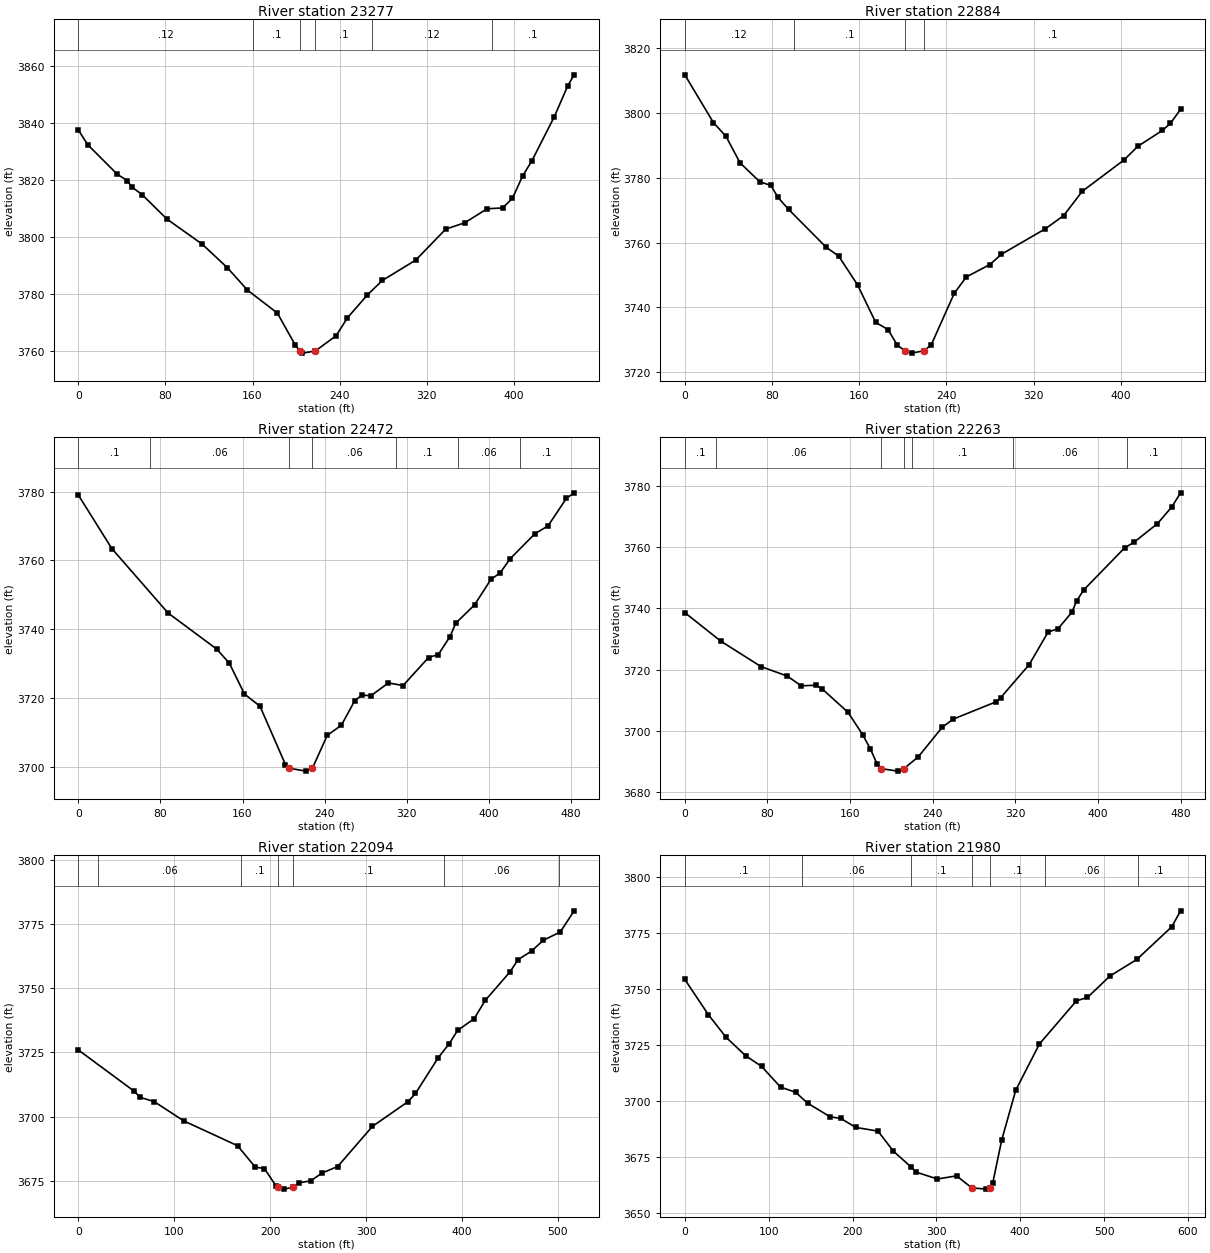
Type RM Length L Ch R = 1 ,23277   ,393.8,393.3,390.6
XS GIS Cut Line= 2
2429345.14997383 709369.868667542429741.30797383 709145.44966754
#Sta/Elev= 30
       0 3837.46     8.6  3832.3    35.7 3821.92    44.9 3819.67    49.4 3817.37
    58.5 3814.77    81.6  3806.1   113.8 3797.34   136.8 3789.11   155.2 3781.26
   182.8 3773.14   199.4 3761.77   203.63759.845   205.8 3759.09  217.663759.847
   236.7  3765.2   247.1 3771.48   265.5 3779.57   279.3 3784.64   309.8 3791.75
   337.3 3802.62   354.9 3804.89   375.4  3809.8   389.6 3810.07   398.6 3813.44
     408 3821.34   416.5 3826.64   437.1 3842.14   449.4 3852.97   455.3 3856.83
#Mann= 6 ,-1,0
       0     .12       0     160      .1       0   203.6    .045       0
  217.66      .1       0     270     .12       0     380      .1       0
Bank Sta=203.6,217.66
XS Rating Curve= 0 ,0
Exp/Cntr=0.3,0.1

Type RM Length L Ch R = 1 ,22884   ,413.7,412.2,410.5
XS GIS Cut Line= 2
2429606.76823493709715.5060260182429933.36323493709398.708026018
#Sta/Elev= 30
       0 3811.85    26.3 3797.08    37.8 3792.84    50.7 3784.67    68.8 3778.81
      79  3777.7    85.5 3773.98    95.3 3770.27   129.7  3758.6   141.3 3755.83
   158.5 3746.98   175.2 3735.37   186.5 3733.17     195 3728.35  202.123726.618
   208.1 3725.89  219.453726.619   226.1 3728.41   247.2 3744.32   258.3 3749.41
   279.9 3753.24   290.6 3756.43   330.8 3764.28   347.7 3768.38   364.7 3775.86
   403.2 3785.59   415.6 3789.74   438.3 3794.68   445.7 3796.89     455 3801.21
#Mann= 4 ,-1,0
       0     .12       0     100      .1       0  202.12    .045       0
  219.45      .1       0
Bank Sta=202.12,219.45
XS Rating Curve= 0 ,0
Exp/Cntr=0.3,0.1

Type RM Length L Ch R = 1 ,22472   ,205.3,208.4,209.6
XS GIS Cut Line= 2
2429947.89810925710003.3960233932430235.37082275709615.108354498
#Sta/Elev= 30
       0    3779    32.6 3763.45    87.4 3744.71   134.9 3734.19   147.1 3730.12
   161.9 3721.13     177  3717.6   201.8 3700.64  205.563699.567   221.7 3698.73
  228.083699.566   242.5 3709.12   256.3 3712.07   269.4 3719.25   276.5 3720.86
   284.9 3720.61   302.1 3724.37   316.4 3723.61   341.2 3731.76   350.7 3732.62
   362.1 3737.81   367.8 3741.78     386 3747.04   402.1 3754.51   410.9 3756.33
   420.8 3760.49     445 3767.79   457.6    3770   475.6 3778.06   483.1 3779.64
#Mann= 7 ,-1,0
       0      .1       0      70     .06       0  205.56    .045       0
  228.08     .06       0     310      .1       0     370     .06       0
     430      .1       0
Bank Sta=205.56,228.08
XS Rating Curve= 0 ,0
Exp/Cntr=0.3,0.1

Type RM Length L Ch R = 1 ,22263   ,178.8,169.2,162.1
XS GIS Cut Line= 3
2430106.12367692710066.3208823062430328.56156872709867.781276402
2430418.63972325709709.684923553
#Sta/Elev= 30
       0 3738.62    34.9 3729.29    73.8 3720.99    99.3 3717.88   112.7  3714.7
   126.9 3714.91   132.6 3713.83   158.1 3706.03   172.2 3698.77   179.7 3694.09
   186.4 3689.03  190.343687.651   206.2 3686.85  212.083687.651   226.1 3691.53
   249.4 3701.23   260.1 3703.86   301.2 3709.46   305.8 3710.82   333.4 3721.61
   351.8 3732.28   361.4 3733.36   374.8 3738.73   379.4 3742.45   386.3 3746.03
   425.9 3759.78   434.7 3761.53   457.7 3767.69   471.5 3773.12   480.1 3777.74
#Mann= 7 ,-1,0
       0      .1       0      30     .06       0  190.34    .045       0
  212.08     .06       0     220      .1       0  318.16     .06       0
  428.16      .1       0
Bank Sta=190.34,212.08
XS Rating Curve= 0 ,0
Exp/Cntr(USF)=0,0
Exp/Cntr=0.3,0.1

Type RM Length L Ch R = 1 ,22094   ,107.8,113.9,125
XS GIS Cut Line= 4
2430262.51879308 710157.956637592430406.58409462710042.704396362
2430390.50238654709886.5778137672430489.00284852709741.172369892
#Sta/Elev= 30
       0 3725.98    58.5 3709.85    64.3 3707.55      79 3705.89   109.9 3698.37
     166 3688.71   184.5 3680.38   194.1 3679.79   206.1 3673.08  208.49 3672.51
   214.2 3671.79  224.333672.509   230.3 3674.26   242.3 3675.01   254.4 3678.11
   270.5  3680.6   306.7 3696.22   343.7 3705.81   351.6 3709.03   375.3 3722.95
   386.9 3728.48   395.5 3733.57   412.8 3738.15   424.3 3745.26   450.2 3756.38
   458.5 3761.11   472.8 3764.53   484.8 3768.66   502.6 3771.92   517.1 3780.16
#Mann= 7 ,-1,0
       0      .1       0      20     .06       0     170      .1       0
  208.49    .045       0  224.33      .1       0  381.45     .06       0
  501.45      .1       0
Bank Sta=208.49,224.33
XS Rating Curve= 0 ,0
Exp/Cntr(USF)=0,0
Exp/Cntr=0.3,0.1

Type RM Length L Ch R = 1 ,21980   ,187.8,190.4,193.4
XS GIS Cut Line= 2
2430275.76310925710250.1195730072430671.24971015709810.561965424
#Sta/Elev= 30
       0 3754.19    28.2 3738.41    49.1  3728.4    72.4 3720.18    91.6 3715.34
   114.2 3706.13   132.2  3703.8   146.5 3698.94   173.4 3692.86     186 3692.14
   203.9 3688.13   230.4 3686.46   248.8  3677.5     270 3670.41   275.7 3668.19
   301.2 3665.11   324.1 3666.49   342.23661.156   359.4 3660.58  363.663661.155
   367.2 3663.22   377.9 3682.45   394.7 3704.77     423 3725.42   467.1 3744.64
   480.2 3746.14   507.1 3755.73   539.1 3763.11   580.7 3777.69   591.3 3784.81
#Mann= 7 ,-1,0
       0      .1       0     140     .06       0     270      .1       0
   342.2    .045       0  363.66      .1       0     430     .06       0
     540      .1       0
Bank Sta=342.2,363.66
XS Rating Curve= 0 ,0
Exp/Cntr=0.3,0.1