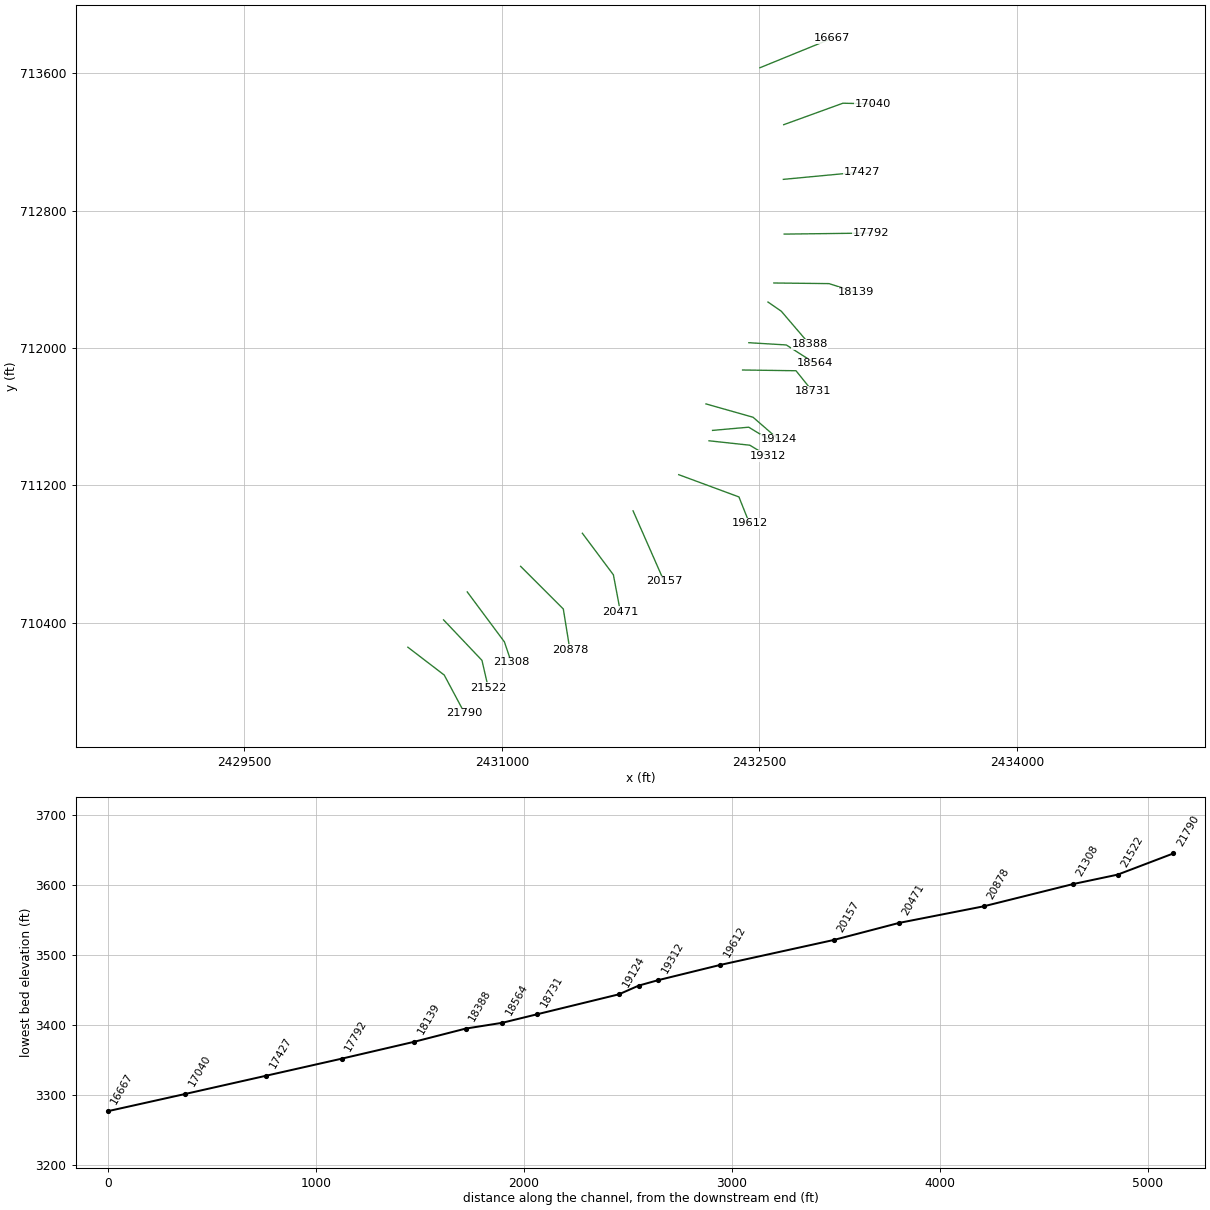
HEC-RAS study SFKREDCK.prj: SFKREDCK

--- SFKREDCK.g01 (geometry) --- (continued)

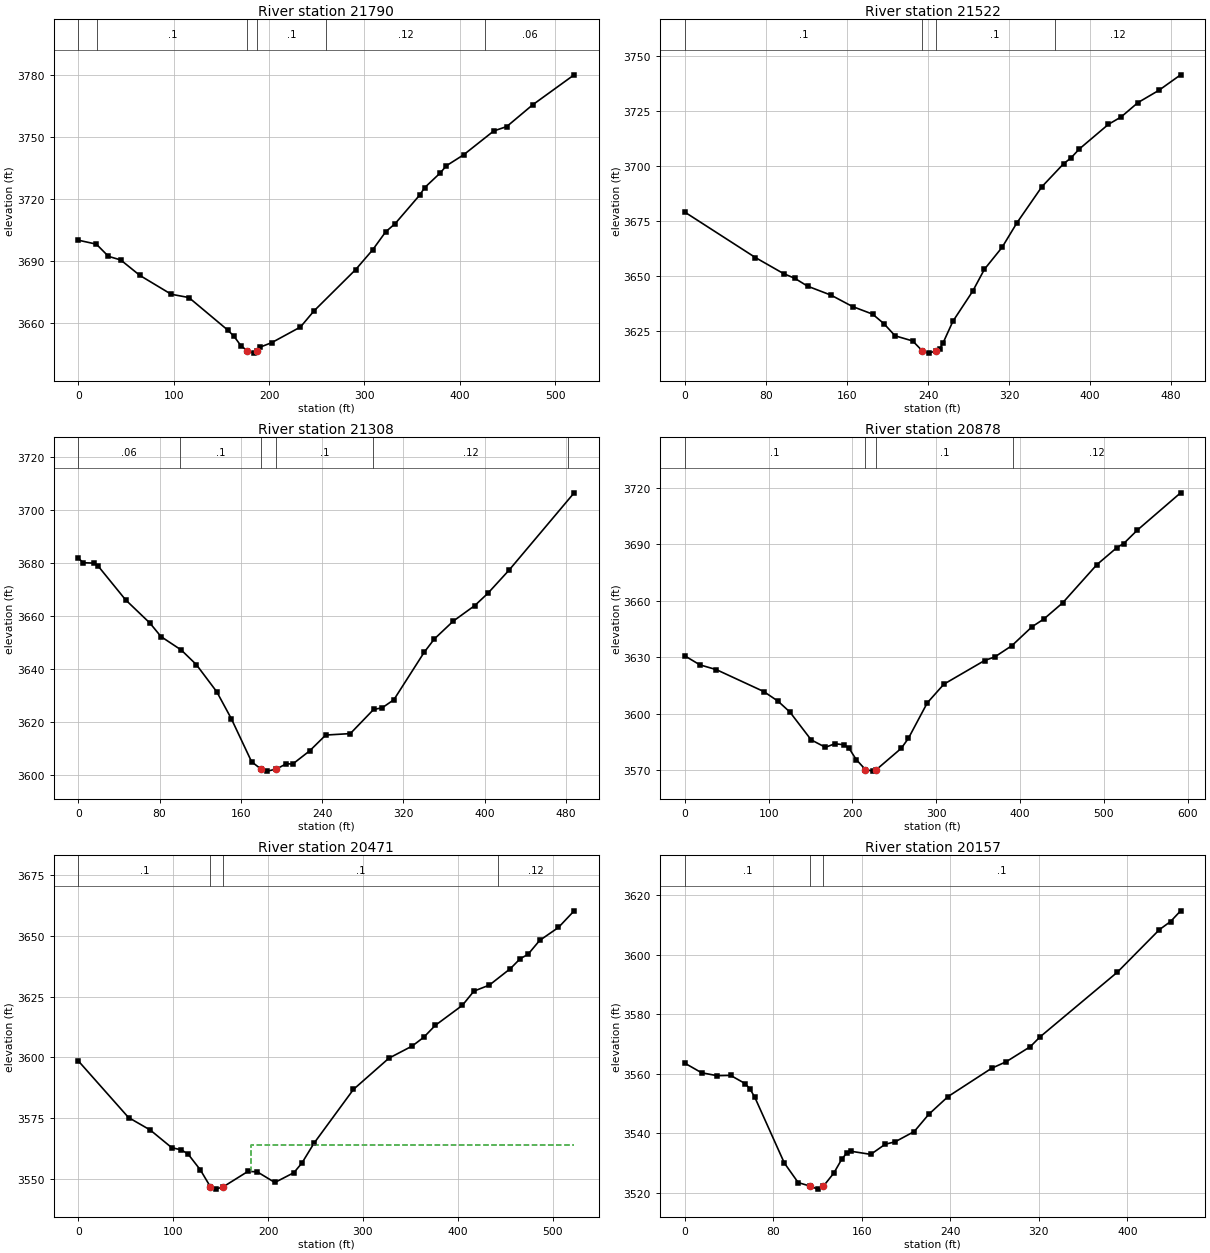
Type RM Length L Ch R = 1 ,21790   ,267.6,268.4,267.1
XS GIS Cut Line= 3
2430452.92207976710256.3747731322430664.69765939710094.234094977
2430783.82142293709870.877038336
#Sta/Elev= 30
       0 3699.89    18.9 3697.97    31.6 3692.05    44.4 3690.33    64.5 3682.83
    97.4  3673.7   115.9 3672.11   156.6 3656.37   163.2 3653.36   170.3 3648.87
  177.223646.225   184.4 3645.18  187.653646.227   190.5 3648.06   202.7 3650.24
   232.9 3657.83   247.1 3665.62   290.8 3685.66   308.5 3695.14   322.3 3703.96
   332.2 3707.91     358 3721.78   363.1 3725.33   379.5 3732.47   385.8 3735.92
   403.9 3741.22   435.6 3752.81   449.2 3754.93   476.4 3765.47   519.9    3780
#Mann= 6 ,-1,0
       0     .06       0      20      .1       0  177.22    .045       0
  187.65      .1       0     260     .12       0  426.72     .06       0
Bank Sta=177.22,187.65
XS Rating Curve= 0 ,0
Exp/Cntr(USF)=0,0
Exp/Cntr=0.3,0.1

Type RM Length L Ch R = 1 ,21522   ,214.2,214,211.2
XS GIS Cut Line= 3
2430660.76896463710415.7750729842430884.39455551710179.839816557
2430921.32355217710019.814164371
#Sta/Elev= 30
       0 3678.98    69.7 3658.29    97.6 3650.95   108.3  3648.9   121.2 3645.26
   144.5 3641.14   165.5 3635.99   185.3 3632.54   196.5 3628.19   207.5 3622.67
   224.9 3620.32  234.553615.727   240.6 3614.78  247.643615.728   251.6 3616.82
     255 3619.57   264.6  3629.3   284.1 3642.96   295.7 3652.97   313.1 3662.93
   327.8 3674.13   352.4 3690.54   373.8 3700.99   381.2  3703.7   389.4 3707.75
   418.1 3718.96   430.5 3722.27   447.2 3728.84   467.7 3734.38   489.3 3741.48
#Mann= 4 ,-1,0
       0      .1       0  234.55    .045       0  247.64      .1       0
  365.08     .12       0
Bank Sta=234.55,247.64
XS Rating Curve= 0 ,0
Exp/Cntr(USF)=0,0
Exp/Cntr=0.3,0.1

Type RM Length L Ch R = 1 ,21308   ,426.4,429,427.4
XS GIS Cut Line= 3
2430798.86609572710578.5337103212431014.92856085710287.822110513
2431055.55111246710168.509269324
#Sta/Elev= 30
       0 3681.81     4.8 3680.06    15.6 3679.93    19.1    3679    46.5 3666.06
    70.5 3657.26    81.4 3652.16   101.4 3647.07   116.2 3641.57   136.3 3631.31
   150.6 3621.17   170.6 3604.88  179.833602.117   186.1 3601.33  194.963602.116
   204.9 3604.14     211 3603.98   227.8    3609   243.6 3614.96   267.8 3615.51
   290.7 3624.62   299.2 3625.26   310.7 3628.31   340.6 3646.27   350.6 3651.29
   369.2 3658.02   390.4  3663.9   403.1 3668.46   424.2 3677.31   488.2 3706.48
#Mann= 6 ,-1,0
       0     .06       0     100      .1       0  179.83    .045       0
  194.96      .1       0     290     .12       0  482.21      .1       0
Bank Sta=179.83,194.96
XS Rating Curve= 0 ,0
Exp/Cntr=0.3,0.1

Type RM Length L Ch R = 1 ,20878   ,407.3,407.3,405.7
XS GIS Cut Line= 3
2431109.50232041710727.7876734132431358.16849766710479.222335624
 2431396.4054118710242.218045779
#Sta/Elev= 30
       0 3630.82    17.9 3626.04    37.7 3623.47    94.2 3611.84   111.2 3606.73
   125.4 3600.95   150.8 3586.15   167.8 3582.19   179.1 3584.09   190.4 3583.53
   196.1  3581.6   204.6 3575.67  215.523570.373   224.4 3569.53  228.753570.374
   258.3 3581.65   266.8 3586.93   289.4 3605.84   309.2 3615.75   357.7 3628.31
   369.9 3630.23   390.3 3636.21   414.4 3646.28   428.4 3650.35   450.9 3658.96
   491.7 3679.26   515.7 3688.36   523.8 3690.51     540 3697.62   591.7 3717.46
#Mann= 4 ,-1,0
       0      .1       0  215.52    .045       0  228.75      .1       0
   391.6     .12       0
Bank Sta=215.52,228.75
XS Rating Curve= 0 ,0
Exp/Cntr=0.3,0.1

Type RM Length L Ch R = 1 ,20471   ,315.2,314.6,312.2
XS GIS Cut Line= 3
2431469.29711113710920.3358710062431649.91299012710678.169958038
2431690.78417244710461.314212137
#Sta/Elev= 30
       0 3598.53    52.9 3575.23    75.8 3570.09    98.5 3562.81   108.7  3561.9
   115.8 3560.14   128.7 3553.65  139.243546.723   145.3 3545.75  152.873546.722
   178.8 3553.04   188.6 3552.88   207.2 3548.48   227.3 3552.53   235.8 3556.52
   248.4 3564.59   290.1 3586.81   327.5 3599.66     352 3604.65   364.2 3608.26
   376.4 3613.17   404.9  3621.4   417.1 3627.26   433.4 3629.75   455.6 3636.54
   465.9  3640.6   474.1 3642.39   486.4 3648.12   506.2 3653.46   522.8 3660.32
#Mann= 4 ,-1,0
       0      .1       0  139.24    .045       0  152.87      .1       0
   442.1     .12       0
#XS Ineff= 2 , 0
                          182.44         3563.72
Permanent Ineff=
       F       F
Bank Sta=139.24,152.87
XS Rating Curve= 0 ,0
Exp/Cntr=0.3,0.1

Type RM Length L Ch R = 1 ,20157   ,537.6,545,551.5
XS GIS Cut Line= 2
2431764.45279608711051.0394330942431945.00524974710640.798907454
#Sta/Elev= 30
       0 3563.63    15.1 3560.42    29.1 3559.42    41.4 3559.52    54.5 3556.77
    58.8 3555.02    63.2 3552.23      90 3530.05   102.5 3523.49   113.3  3522.3
     120 3521.29  125.323522.299   134.7 3526.68   141.9 3531.35   146.3 3533.39
   150.6    3534   168.1 3532.97   181.2 3536.39     190 3537.17   207.4 3540.65
   220.5 3546.42     238 3552.41   277.3  3561.9   290.5  3564.1   312.3 3569.17
   321.1 3572.45     391  3594.2   429.1 3608.53   439.1 3611.23   448.2 3614.83
#Mann= 3 ,-1,0
       0      .1       0   113.3    .045       0  125.32      .1       0
Bank Sta=113.3,125.32
XS Rating Curve= 0 ,0
Exp/Cntr=0.3,0.1

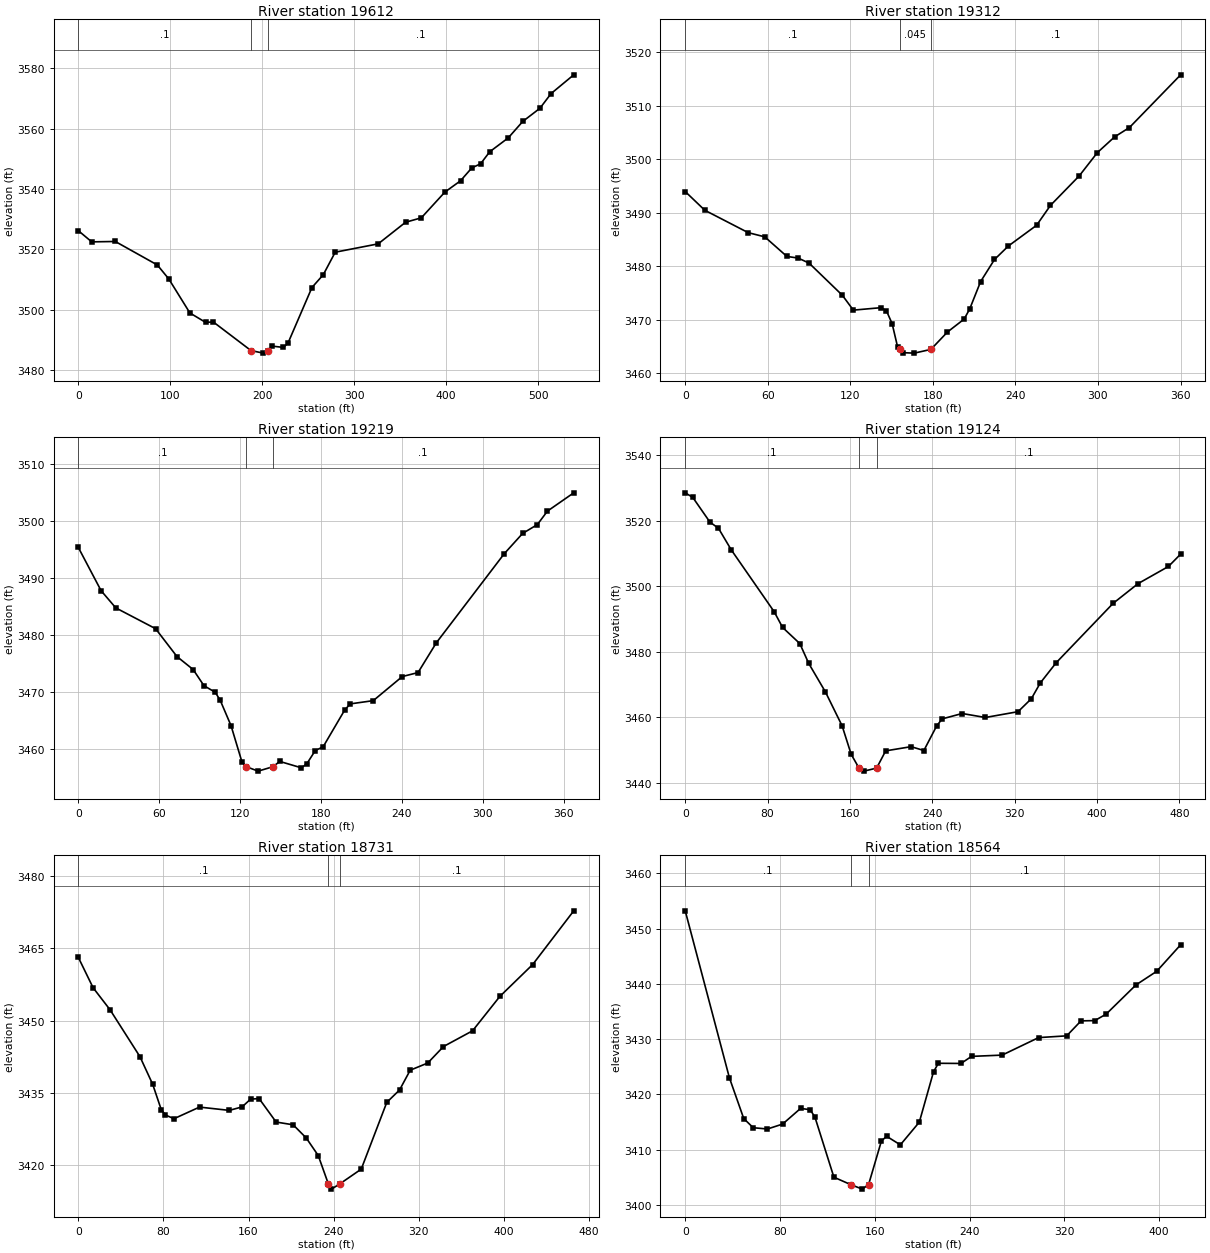
Type RM Length L Ch R = 1 ,19612   ,294.8,299.6,301.6
XS GIS Cut Line= 3
2432030.45554577711261.8863201032432381.00953908711132.165180773
2432441.92737854710978.972822933
#Sta/Elev= 30
       0 3526.19    14.6 3522.48    40.2 3522.61    85.9 3514.83    98.4 3510.19
   121.3 3498.94   138.3 3495.84   146.8 3495.95   187.7 3486.49   201.1 3485.64
  206.183486.489   210.8 3487.96   222.9 3487.53   227.9 3488.92     254 3507.37
   266.3  3511.6   279.3 3519.06     326 3521.82   355.8 3528.98   372.9 3530.44
   398.5 3538.96   415.5  3542.7   427.8 3546.98   437.3 3548.32   447.3 3552.32
   467.4 3556.91   483.2 3562.36   501.8  3566.7     514 3571.59   538.6 3577.79
#Mann= 3 ,-1,0
       0      .1       0   187.7    .045       0  206.18      .1       0
Bank Sta=187.7,206.18
XS Rating Curve= 0 ,0
Exp/Cntr=0.3,0.1

Type RM Length L Ch R = 1 ,19312   ,89.2,92.4,93.9
XS GIS Cut Line= 3
2432206.68882587711459.3657418342432444.36988729711433.600857128
2432548.07354823711371.121011715
#Sta/Elev= 30
       0 3493.93    14.2 3490.44    45.8 3486.25    57.8 3485.47    73.9 3481.81
      82 3481.51      90 3480.57   114.2 3474.56   122.2 3471.78   142.3 3472.24
   146.3 3471.63   150.4 3469.25   154.4 3464.87   155.93464.448   158.4 3463.83
   166.5 3463.75  178.583464.447   190.6 3467.69   202.7  3470.1   206.7 3471.95
   214.7 3477.11   224.8 3481.24   234.9 3483.76   255.4 3487.63   265.5 3491.35
   286.4 3496.86   299.6 3501.21   312.1 3504.14   322.9 3505.89   360.1 3515.73
#Mann= 3 ,-1,0
       0      .1       0   155.9    .045       0  178.58      .1       0
Bank Sta=155.9,178.58
XS Rating Curve= 0 ,0
Exp/Cntr(USF)=0,0
Exp/Cntr=0.3,0.1

Type RM Length L Ch R = 1 ,19219   ,98,95.2,91.6
XS GIS Cut Line= 3
2432227.30073364711519.9132208942432437.92866611711538.592762306
2432571.26194446711457.433375481
#Sta/Elev= 30
       0 3495.34    16.9 3487.74    27.8 3484.72    57.3 3481.07    73.2 3476.17
    85.2 3473.89    93.2 3471.06   101.6 3469.89   105.3 3468.47   113.3 3464.03
   121.3 3457.73  124.72 3456.81   133.4 3456.05  144.18 3456.81   149.5 3457.75
   165.5 3456.63   169.5 3457.34   175.8 3459.67   181.6 3460.32   197.6 3466.78
   201.7 3467.86   218.8 3468.43   240.3 3472.66     252 3473.36   265.6  3478.6
     316 3494.25   329.6  3497.8   340.5 3499.35     348 3501.72   367.5 3504.93
#Mann= 3 ,-1,0
       0      .1       0  124.72    .045       0  144.18      .1       0
Bank Sta=124.72,144.18
XS Rating Curve= 0 ,0
Exp/Cntr(USF)=0,0
Exp/Cntr=0.3,0.1

Type RM Length L Ch R = 1 ,19124   ,390.1,393.2,389.1
XS GIS Cut Line= 3
2432189.12482853711674.275182733 2432463.2390879711596.590011666
 2432611.3089047 711467.71048267
#Sta/Elev= 30
       0 3528.58     7.3  3527.2      24 3519.64    32.3 3517.75    44.7 3511.17
    86.3 3492.31    94.6 3487.46   111.3 3482.54     120 3476.46   136.2 3467.76
   152.4 3457.41   161.2  3448.7   168.83444.506   173.6 3443.58   185.93444.505
   194.7 3449.77   219.4 3451.05   231.8 3449.88   244.3 3457.43   249.6 3459.54
     269 3461.18   291.5 3459.96   323.3 3461.74   336.2  3465.7   344.9 3470.52
   360.4 3476.72   415.6 3494.82   439.9 3500.86   469.4  3506.1   481.2 3509.86
#Mann= 3 ,-1,0
       0      .1       0   168.8    .045       0   185.9      .1       0
Bank Sta=168.8,185.9
XS Rating Curve= 0 ,0
Exp/Cntr=0.3,0.1

Type RM Length L Ch R = 1 ,18731   ,166.7,167.6,164.3
XS GIS Cut Line= 3
2432402.29912705711871.8717140552432713.28214737711867.578361601
 2432810.1118447711747.127328576
#Sta/Elev= 30
       0  3463.1    13.9  3456.8    29.9 3452.21    57.9 3442.52    69.9 3436.78
    77.9 3431.55    81.9 3430.41    89.9 3429.64   113.9 3432.05   141.9 3431.37
   153.9 3432.09   161.9  3433.7   169.9 3433.82   185.9 3428.95   201.9 3428.38
   214.2 3425.65   225.5    3422  234.873416.192   237.9 3415.04  246.18 3416.19
   265.9 3419.19   289.9 3433.03   301.9  3435.6   311.9  3439.7   328.4 3441.19
   343.2 3444.61   370.5 3447.87   396.2 3455.01     427 3461.61   465.6 3472.75
#Mann= 3 ,-1,0
       0      .1       0  234.87    .045       0  246.18      .1       0
Bank Sta=234.87,246.18
XS Rating Curve= 0 ,0
Exp/Cntr=0.3,0.1

Type RM Length L Ch R = 1 ,18564   ,181.1,176,170
XS GIS Cut Line= 3
2432438.90770166712030.9353262192432656.63033526712017.883844592
2432825.21648943711910.066945517
#Sta/Elev= 30
       0 3453.23    37.3 3422.99    49.4 3415.61    57.4 3413.95    69.4 3413.72
    82.2 3414.61    97.4 3417.45   105.5 3417.21   109.5 3415.87   125.5 3404.99
  139.553403.665   149.5 3402.83  154.793403.664   165.6 3411.54     170  3412.4
   181.6 3410.85   197.6 3414.96   209.6 3424.08   213.7 3425.62   232.8 3425.59
   241.7 3426.87   267.5  3427.1   298.3 3430.27     322 3430.59   334.1  3433.3
   345.7 3433.35   355.3 3434.52   380.5 3439.81     398 3442.28   418.2 3447.08
#Mann= 3 ,-1,0
       0      .1       0  139.55    .045       0  154.79      .1       0
#XS Ineff= 2 , 0
                          469.92         3452.17
Permanent Ineff=
       F       F
Bank Sta=139.55,154.79
XS Rating Curve= 0 ,0
Exp/Cntr=0.3,0.1

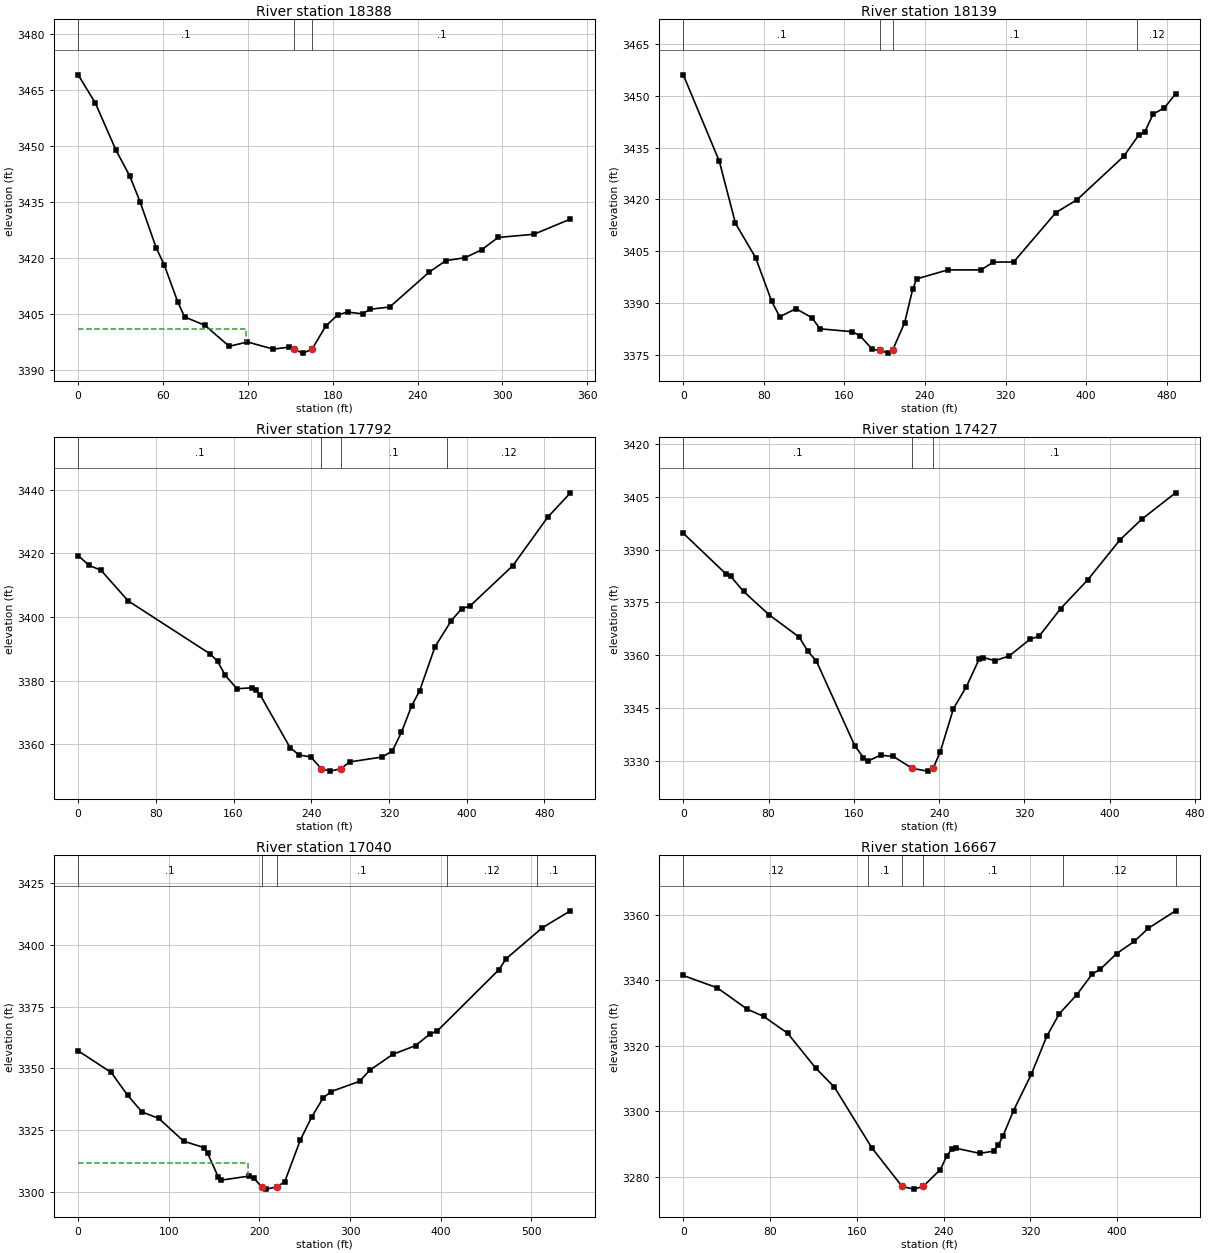
Type RM Length L Ch R = 1 ,18388   ,242.1,248.8,253.1
XS GIS Cut Line= 3
2432550.17033017712267.9787073912432627.30594179712214.699470498
2432792.71013991712021.462835201
#Sta/Elev= 30
       0 3469.12    12.2 3461.52    26.7 3448.96    36.5 3441.99    43.7 3435.16
    55.2 3422.74      61 3418.05    70.5 3408.17    75.3 3404.23    89.7 3401.97
   106.8 3396.36   119.7 3397.52     138  3395.6   149.3 3396.15  152.27 3395.57
   158.9 3394.53  165.413395.584     175 3401.75   183.4 3404.76   190.5 3405.53
   201.1 3405.05   206.3 3406.29   220.3 3406.88   248.4  3416.3     260 3419.32
   273.5  3420.1   285.3 3422.23   296.9 3425.53   322.2 3426.38   348.1 3430.46
#Mann= 3 ,-1,0
       0      .1       0  152.27    .045       0  165.41      .1       0
#XS Ineff= 2 , 0
          118.44 3400.91
Permanent Ineff=
       F       F
Bank Sta=152.27,165.41
XS Rating Curve= 0 ,0
Exp/Cntr(USF)=0,0
Exp/Cntr=0.3,0.1

Type RM Length L Ch R = 1 ,18139   ,343.1,346.8,346.8
XS GIS Cut Line= 3
2432584.40326215712378.9269794322432905.43903202712375.292612226
2433065.35118909712324.411471341
#Sta/Elev= 30
       0 3456.05    35.8 3431.04    51.8  3413.1    71.8 3403.18    87.8 3390.51
    95.8 3386.03   111.8 3388.41   127.8 3385.78   135.8 3382.57   167.8 3381.74
   175.8  3380.5   187.8  3376.6   195.3 3376.33   203.8 3375.54   207.8 3376.36
   219.8 3384.32   227.8 3393.99   231.8 3397.02   262.6 3399.61   295.8 3399.62
   307.8 3401.87   328.1 3401.91   370.1 3416.21   391.1 3419.93   437.3 3432.44
   452.3 3438.61   458.3 3439.51   466.6 3444.69   477.8  3446.5   488.9 3450.54
#Mann= 4 ,-1,0
       0      .1       0   195.3    .045       0   207.8      .1       0
  451.06     .12       0
Bank Sta=195.3,207.8
XS Rating Curve= 0 ,0
Exp/Cntr(USF)=0,0
Exp/Cntr=0.3,0.1

Type RM Length L Ch R = 1 ,17792   ,362.8,364.8,364.6
XS GIS Cut Line= 2
2432644.67980938712663.840508354 2433151.5034716712669.931938689
#Sta/Elev= 30
       0 3419.27    11.5 3416.19    23.5 3414.69    51.5 3405.05   135.8  3388.4
   143.5 3386.07   151.5 3381.63   163.5 3377.43   179.5 3377.74   183.5  3376.9
   187.5 3375.45   218.2 3358.91   227.5 3356.59   239.5    3356  250.213352.318
   259.5 3351.52  270.723352.317   279.5 3354.42   313.1 3355.95   323.5 3357.86
   332.9 3363.74   343.5 3372.13   351.5 3376.72   367.5 3390.67   384.2 3398.82
   394.9 3402.61   403.5 3403.44   447.6 3416.14   483.5 3431.37   506.9 3439.03
#Mann= 4 ,-1,0
       0      .1       0  250.21    .045       0  270.72      .1       0
     380     .12       0
Bank Sta=250.21,270.72
XS Rating Curve= 0 ,0
Exp/Cntr=0.3,0.1

Type RM Length L Ch R = 1 ,17427   ,384.1,387.6,388.2
XS GIS Cut Line= 2
 2432639.9490892712982.816945373 2433099.5500892713026.326945373
#Sta/Elev= 30
       0 3394.65    40.4 3382.97    44.4 3382.43    56.5 3378.11    80.6 3371.43
   108.7 3365.12   116.7 3361.14   124.8 3358.32   160.9 3334.19     169 3330.84
     173 3329.85     185 3331.54   197.1 3331.17  214.773327.783   229.2 3327.01
  234.253327.785     241 3332.49   253.4  3344.8   265.4 3350.95   277.5 3358.87
   281.5 3359.31   292.3  3358.4   305.6 3359.74   325.4 3364.56   333.7 3365.35
   353.8 3373.19   379.3 3381.39   409.8 3392.86   430.1 3398.66   461.7 3406.14
#Mann= 3 ,-1,0
       0      .1       0  214.77    .045       0  234.25      .1       0
Bank Sta=214.77,234.25
XS Rating Curve= 0 ,0
Exp/Cntr=0.3,0.1

Type RM Length L Ch R = 1 ,17040   ,371.9,372.8,372.7
XS GIS Cut Line= 3
2432641.89441421713301.4515645882432986.56504968713426.599831041
2433163.00358927 713422.49660919
#Sta/Elev= 30
       0  3357.1    36.5 3348.32    54.6 3339.06    70.5  3332.3      89 3329.67
   116.4 3320.45   138.6 3317.87   142.9 3315.49   154.5    3306   157.7 3304.64
   188.9 3306.31   193.9 3305.44  202.423301.947   207.6    3301  219.563301.947
     228 3304.06   245.3 3321.06   257.8 3330.34   270.5 3338.08   279.4  3340.6
   310.6 3344.76   321.6 3349.19   347.1 3355.65   372.3 3359.22   388.3 3363.96
   396.3 3365.18   464.3 3390.02   472.3 3394.48   512.3 3407.06   543.2 3413.89
#Mann= 5 ,-1,0
       0      .1       0  202.42    .045       0  219.56      .1       0
  406.69     .12       0  506.69      .1       0
#XS Ineff= 2 , 0
          187.13 3311.47
Permanent Ineff=
       F       F
Bank Sta=202.42,219.56
XS Rating Curve= 0 ,0
Exp/Cntr(USF)=0,0
Exp/Cntr=0.3,0.1

Type RM Length L Ch R = 1 ,16667   ,283.3,282,277.2
XS GIS Cut Line= 2
2432503.13904126713633.2426388182432923.41404126713804.657638818
#Sta/Elev= 30
       0 3341.41    31.4 3337.64      59 3331.13      74 3328.96    96.2 3323.82
   122.1 3313.19   139.4 3307.35   173.9 3288.86  201.773277.113   212.5  3276.3
  221.173277.113     237 3282.27     243 3286.42   247.4 3288.45   251.7 3288.74
   273.3 3287.21   286.2 3287.87   290.6 3289.79   294.9 3292.63   304.5 3300.23
   320.8 3311.25   335.2 3322.92   346.7 3329.75   362.8 3335.55     377 3341.84
   384.3 3343.25   399.6  3348.1   415.8  3351.8   428.8 3355.81   453.9 3361.12
#Mann= 6 ,-1,0
       0     .12       0     170      .1       0  201.77    .045       0
  221.17      .1       0     350     .12       0  453.89      .1       0
Bank Sta=201.77,221.17
XS Rating Curve= 0 ,0
Exp/Cntr=0.3,0.1