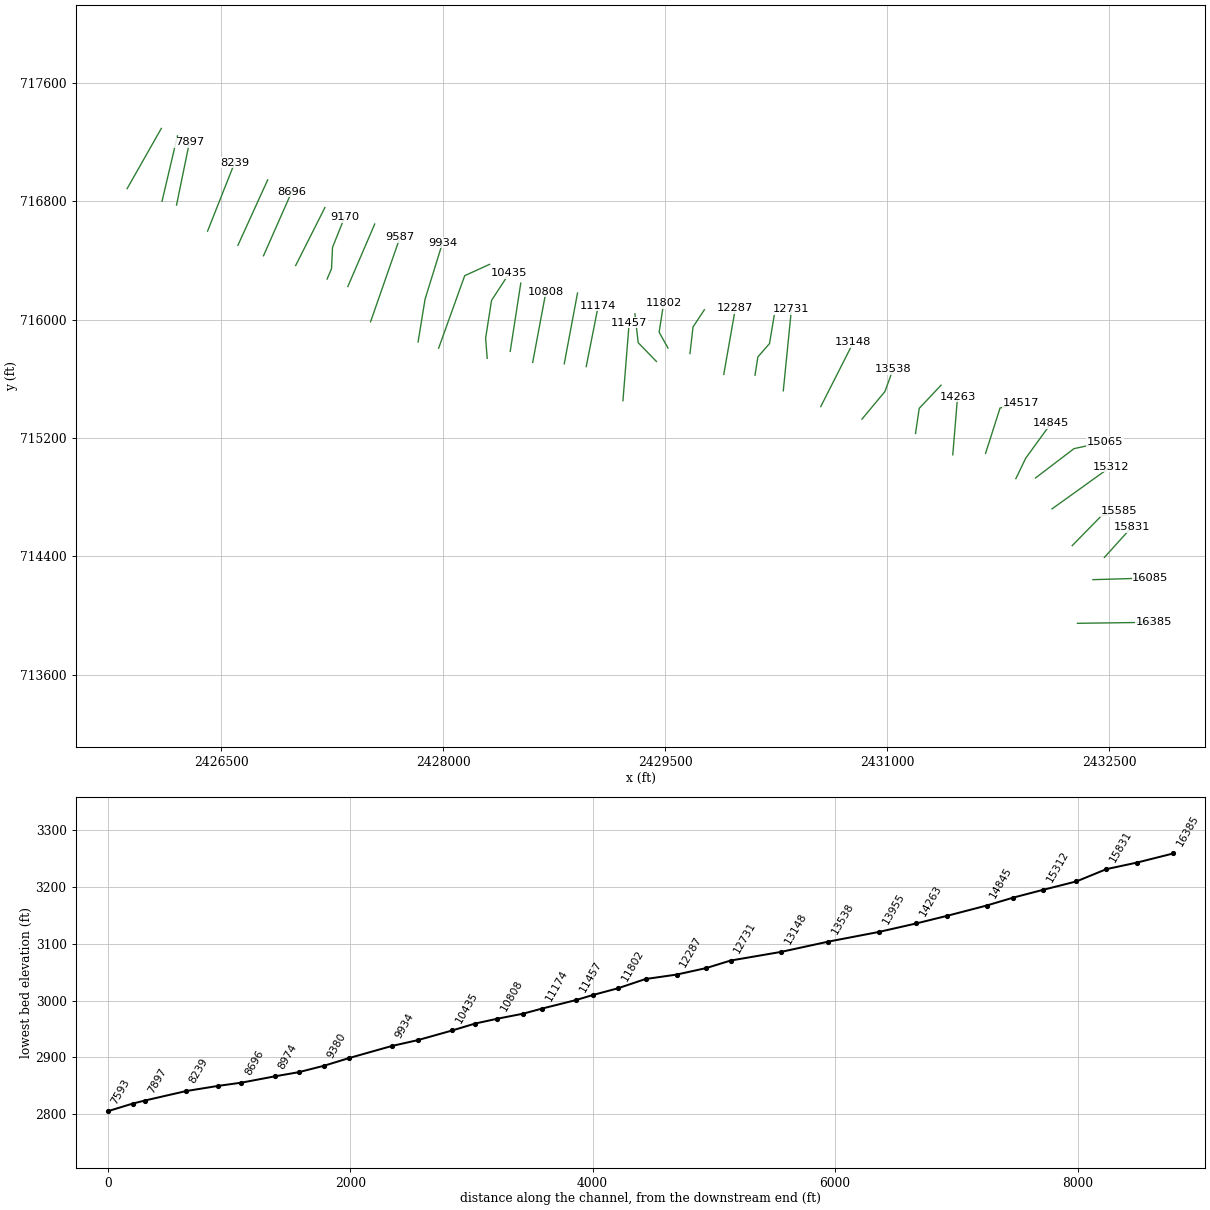
HEC-RAS study SFKREDCK.prj: SFKREDCK

--- SFKREDCK.g01 (geometry) --- (continued)

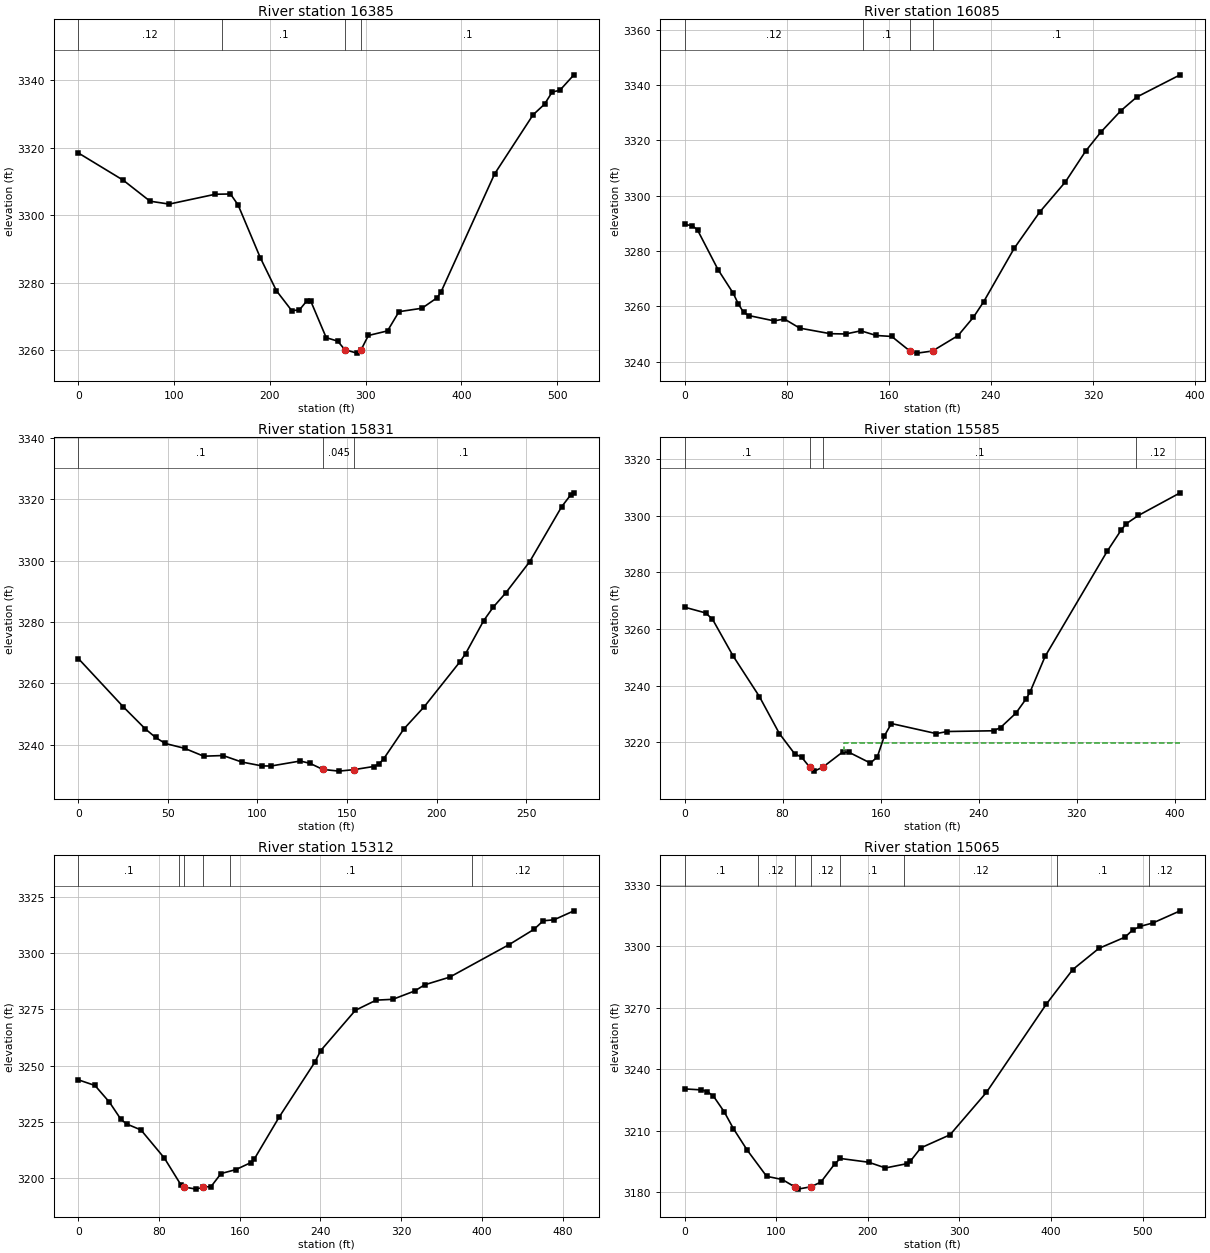
Type RM Length L Ch R = 1 ,16385   ,299.1,299.4,299.4
XS GIS Cut Line= 2
2432285.31735508713947.4621036222432802.90874281713954.447678863
#Sta/Elev= 30
       0 3318.42    46.9 3310.35    74.9 3304.14    94.9 3303.28   143.1  3306.2
   158.9 3306.27   166.9    3303     190 3287.44   206.9 3277.63   222.9 3271.74
   230.9 3271.95   238.9 3274.72   242.9 3274.46   258.9 3263.74   270.9 3262.71
   278.3 3260.19   290.9 3259.16  295.413260.191   302.9 3264.38   322.9 3265.74
   334.9 3271.43   358.9 3272.45   374.9 3275.59   378.9 3277.34   434.7 3312.19
   474.9  3329.7   486.9 3332.86   494.9 3336.46   502.9 3336.97   517.6 3341.55
#Mann= 4 ,-1,0
       0     .12       0     150      .1       0   278.3    .045       0
  295.41      .1       0
Bank Sta=278.3,295.41
XS Rating Curve= 0 ,0
Exp/Cntr=0.3,0.1

Type RM Length L Ch R = 1 ,16085   ,250.9,254,264.6
XS GIS Cut Line= 2
2432389.99211952714242.4871791792432778.15520484714253.984858959
#Sta/Elev= 30
       0 3289.57     6.2 3289.13    10.2 3287.54    26.2 3273.29    38.2 3264.67
    42.2 3260.78    46.2 3257.86    50.2 3256.67    70.2 3254.73    78.2 3255.42
    90.2 3252.12   114.2  3250.1   126.2    3250   138.2 3251.14   150.2 3249.45
   162.3 3249.11  176.523243.852   182.3 3243.08   194.3 3243.85   214.3 3249.42
   226.3 3256.03   234.3  3261.6   258.3 3280.97   278.3 3294.08   298.3 3304.89
   314.3 3316.11   326.3 3323.01   341.8 3330.65   354.3 3335.61   388.3 3343.64
#Mann= 4 ,-1,0
       0     .12       0     140      .1       0  176.52    .045       0
   194.3      .1       0
Bank Sta=176.52,194.3
XS Rating Curve= 0 ,0
Exp/Cntr=0.3,0.1

Type RM Length L Ch R = 1 ,15831   ,247.6,246.4,251
XS GIS Cut Line= 2
2432467.35052438714393.1842202022432652.75684933714598.646463997
#Sta/Elev= 30
       0 3268.12    25.1 3252.39    37.4  3245.2    43.1 3242.44    48.5 3240.47
    59.3 3238.89      70 3236.32    80.8 3236.54    91.2 3234.43   102.7 3233.14
   107.7 3233.14   123.9 3234.75   129.3    3234   136.5 3232.02   145.5 3231.46
   154.1 3231.96   164.8 3232.96   167.7 3233.69   170.5 3235.48   181.8 3245.22
   193.2 3252.48     213 3267.01   216.2 3269.68   226.3 3280.44   231.7 3284.88
   238.5 3289.38     252 3299.64   269.9 3317.58   274.8 3321.31   276.7 3322.06
#Mann= 3 ,-1,0
       0      .1       0   136.5    .045       0   154.1      .1       0
Bank Sta=136.5,154.1
XS Rating Curve= 0 ,0
Exp/Cntr(USF)=0,0
Exp/Cntr=0.3,0.1

Type RM Length L Ch R = 1 ,15585   ,273.1,273.5,273.2
XS GIS Cut Line= 3
2432250.03672745714472.9214030232432444.93976536714671.927662793
2432566.60391938714704.609963642
#Sta/Elev= 30
       0 3267.69    17.2 3265.66    22.8 3263.45    39.6 3250.51    61.1 3236.17
    77.4 3223.12    89.9 3215.97    95.5 3214.82  102.073211.321     106 3209.88
  113.013211.322   129.1 3216.64   134.5 3216.46   151.7 3212.72   157.3 3214.86
   163.1  3222.3   168.8 3226.66   205.4 3223.12   214.6 3223.85   252.3 3224.11
   257.9 3225.25   270.4  3230.3   278.6 3235.26   281.9 3237.68   294.3 3250.35
     345 3287.44   356.5 3294.98   360.6 3297.14   370.4 3300.02   404.5 3308.01
#Mann= 4 ,-1,0
       0      .1       0  102.07    .045       0  113.01      .1       0
  368.55     .12       0
#XS Ineff= 2 , 0
                          130.12         3219.88
Permanent Ineff=
       F       F
Bank Sta=102.07,113.01
XS Rating Curve= 0 ,0
Exp/Cntr(USF)=0,0
Exp/Cntr=0.3,0.1

Type RM Length L Ch R = 1 ,15312   ,248.1,246.9,248
XS GIS Cut Line= 2
2432113.33863489714720.9482413452432512.27213657715007.540176693
#Sta/Elev= 30
       0 3243.68    16.5 3241.16    30.9 3233.71    42.3 3226.07    47.8 3224.08
    62.1 3221.41    85.3 3208.91     102  3196.8  104.953196.057   116.8 3195.13
  124.053196.057   131.5 3196.23   141.4 3202.04   156.2 3203.81   170.9 3206.89
   174.2 3208.34   199.2 3227.24   234.4  3251.5   240.3 3256.69   274.6 3274.55
   295.2 3279.06   311.7 3279.43   333.5 3283.16   343.3 3285.88     368 3289.26
   427.1 3303.76   451.7 3310.53   460.8 3314.32   471.4 3314.73   491.2 3318.73
#Mann= 6 ,-1,0
       0      .1       0     100     .12       0  104.95    .045       0
  124.05     .12       0     150      .1       0     390     .12       0
Bank Sta=104.95,124.05
XS Rating Curve= 0 ,0
Exp/Cntr=0.3,0.1

Type RM Length L Ch R = 1 ,15065   ,217.8,220,223.8
XS GIS Cut Line= 3
2432001.79615535714930.0179519882432261.78376928715128.359018286
2432470.84597429 715173.92385784
#Sta/Elev= 30
       0 3230.39    18.4 3229.91      25 3229.03    31.6 3226.82    43.2 3219.27
    53.3 3211.01    68.4 3200.47    89.6 3187.67   106.7 3186.11  120.113182.555
   123.7 3181.41  137.923182.555   148.9 3184.88     164 3193.79   170.1 3196.39
   200.9 3194.56   219.3 3191.76   242.6 3193.83   246.5 3195.07   257.9 3201.56
   289.8 3207.97   329.5 3228.67     395 3271.88   423.8 3288.74   452.3 3299.08
   480.9 3304.58   489.1 3308.05   497.3 3309.83   511.2 3311.49     541 3317.43
#Mann= 8 ,-1,0
       0      .1       0      80     .12       0  120.11    .045       0
  137.92     .12       0     170      .1       0     240     .12       0
  407.01      .1       0  507.01     .12       0
Bank Sta=120.11,137.92
XS Rating Curve= 0 ,0
Exp/Cntr(USF)=0,0
Exp/Cntr=0.3,0.1

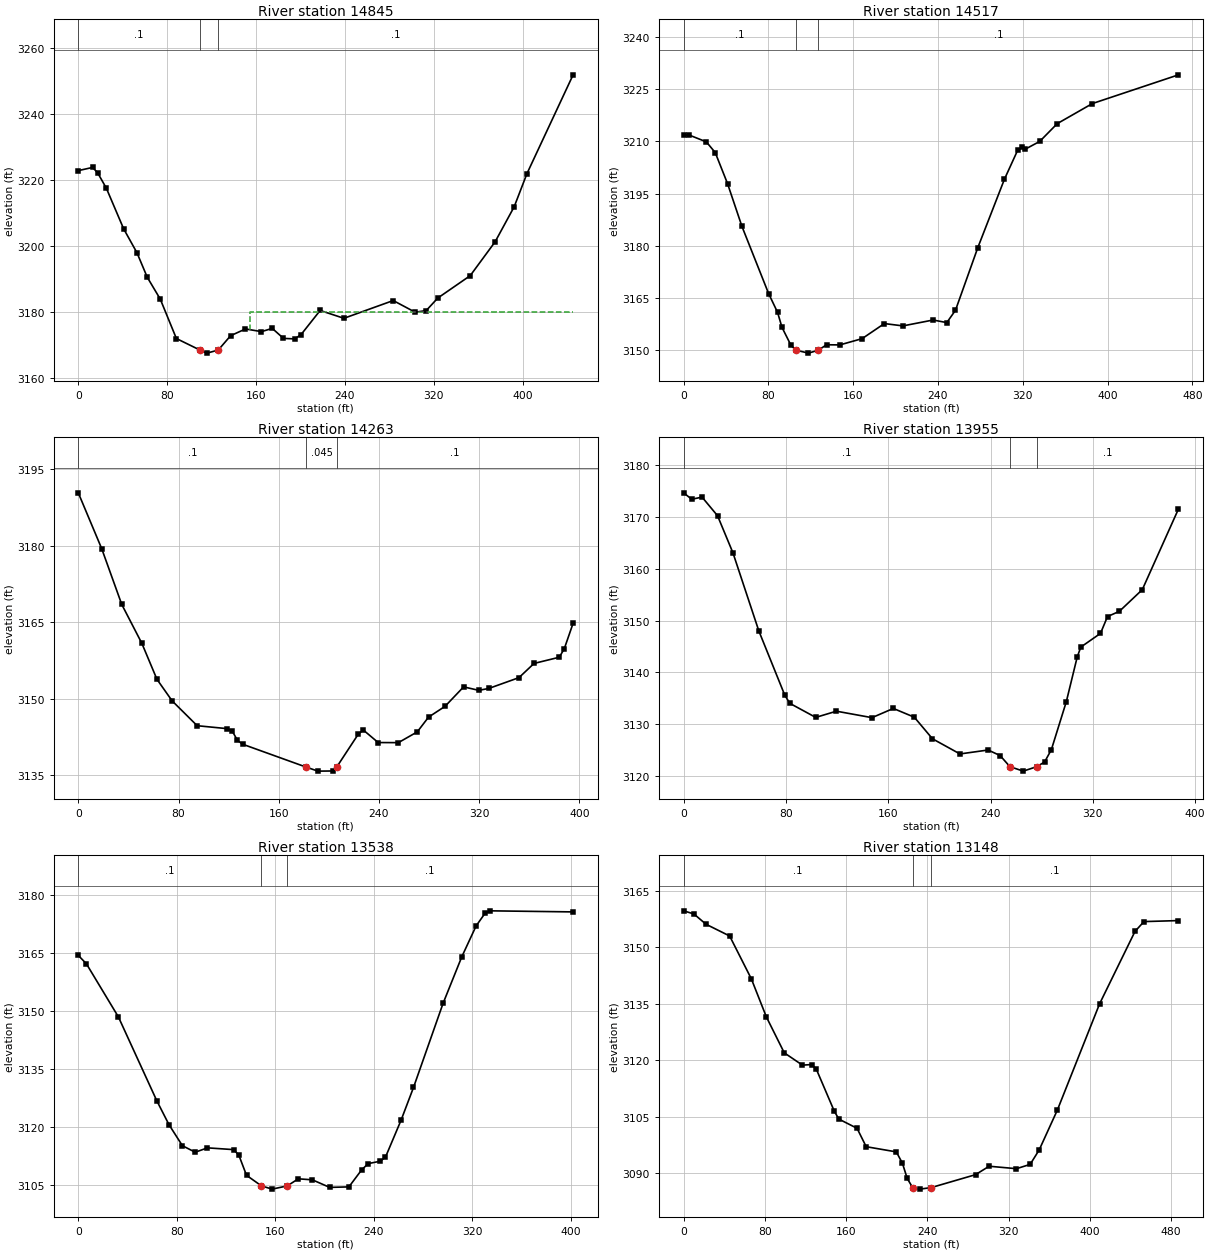
Type RM Length L Ch R = 1 ,14845   ,320.1,327.9,325
XS GIS Cut Line= 3
2431869.20378931714925.6326722632431935.91359209715064.116619293
2432107.31194785715300.184208867
#Sta/Elev= 30
       0 3222.74    12.8  3223.7    17.3 3222.15    25.3 3217.38    40.8 3205.12
    52.8 3197.85    62.1  3190.4    73.8 3183.78    88.3 3171.84  109.513168.344
   115.8 3167.41  125.993168.343   137.1 3172.69   150.5 3174.74   164.9 3173.93
   174.6 3174.91   184.7 3171.88   194.8 3171.72   200.5 3173.02   217.7 3180.34
   239.1 3177.97   283.5 3183.35   303.3  3179.8   313.2 3180.32   323.6 3184.11
   352.8  3190.9   375.2 3201.16   392.4 3211.81   403.8 3221.79   445.4 3251.78
#Mann= 3 ,-1,0
       0      .1       0  109.51    .045       0  125.99      .1       0
#XS Ineff= 2 , 0
                           154.8            3180
Permanent Ineff=
       F       F
Bank Sta=109.51,125.99
XS Rating Curve= 0 ,0
Exp/Cntr=0.3,0.1

Type RM Length L Ch R = 1 ,14517   ,250.6,253.5,256.1
XS GIS Cut Line= 3
2431664.56370077715096.7894578812431762.42554192715403.300130144
2431902.75572922715440.229126802
#Sta/Elev= 30
       0 3211.75     4.6 3211.91    21.4 3209.88    29.8 3206.81    41.4  3197.9
      55 3185.61    80.2 3166.29    88.6 3160.93    92.8  3156.6   101.2  3151.5
  105.883150.059   117.8 3149.21  127.15 3150.06   134.8 3151.61   147.4 3151.57
   168.4 3153.37   189.4  3157.7   206.9 3157.03   235.4 3158.72   248.3 3157.98
   256.5 3161.52   277.5 3179.45   302.7 3199.16   315.3 3207.56   319.5 3208.33
   321.8 3207.69     336 3210.01   352.5 3215.11   385.6 3220.87   466.9 3229.13
#Mann= 3 ,-1,0
       0      .1       0  105.88    .045       0  127.15      .1       0
Bank Sta=105.88,127.15
XS Rating Curve= 0 ,0
Exp/Cntr(USF)=0,0
Exp/Cntr=0.3,0.1

Type RM Length L Ch R = 1 ,14263   ,313.7,307.7,297.1
XS GIS Cut Line= 2
2431442.91715863715086.5618045912431475.31470455715480.241074785
#Sta/Elev= 30
       0 3190.38    18.7 3179.44    34.7 3168.51    50.8 3160.86    62.8 3153.84
    74.9 3149.62    94.9 3144.75     119 3144.17     123 3143.66     127  3141.9
   131.1 3141.13   182.13136.621   191.3 3135.85   203.3 3135.88  206.21 3136.62
   223.4 3143.05   227.4 3143.93   239.4 3141.45   255.5 3141.43   270.6 3143.54
   279.6 3146.43   292.8 3148.55   307.6 3152.36   319.7 3151.68   327.7 3152.05
   351.8 3154.17   363.8 3156.95   383.9 3158.16   387.9 3159.79     395 3164.83
#Mann= 3 ,-1,0
       0      .1       0   182.1    .045       0  206.21      .1       0
Bank Sta=182.1,206.21
XS Rating Curve= 0 ,0
Exp/Cntr(USF)=0,0
Exp/Cntr=0.3,0.1

Type RM Length L Ch R = 1 ,13955   ,416,417,417.8
XS GIS Cut Line= 3
2431191.18548037715230.9704167962431216.21827624 715400.90930225
2431363.85514068 715557.57682949
#Sta/Elev= 30
       0 3174.68     6.3 3173.44    14.4 3173.85    26.5 3170.26    38.6 3163.06
    58.8    3148    79.1 3135.58    83.1    3134   103.3 3131.29   119.5 3132.49
   147.3 3131.24     164 3133.02   180.4 3131.33   194.6 3127.16   216.1 3124.23
   238.1 3124.99   247.5 3123.92  255.183121.772   265.6 3120.91  276.183121.771
   282.3 3122.68   287.6 3125.06   299.3 3134.34   307.8 3142.95   310.6 3144.87
     326 3147.52   331.5 3150.77   340.8 3151.79   358.7 3155.97     387 3171.56
#Mann= 3 ,-1,0
       0      .1       0  255.18    .045       0  276.18      .1       0
Bank Sta=255.18,276.18
XS Rating Curve= 0 ,0
Exp/Cntr=0.3,0.1

Type RM Length L Ch R = 1 ,13538   ,386.3,390,390.8
XS GIS Cut Line= 3
2430829.35842474715328.139408574 2430984.4564202715514.470079336
 2431039.1870759715664.412816662
#Sta/Elev= 30
       0  3164.4     6.6 3162.22    32.6 3148.46    63.8 3126.75    73.7 3120.56
    84.6 3115.11      95 3113.42     105 3114.55   126.3 3114.09   130.5 3112.64
   136.7 3107.44  148.79 3104.71   157.5 3103.86  169.85  3104.7   178.8 3106.53
   190.2 3106.27   204.3 3104.31   219.9 3104.44   230.3 3108.86   235.6 3110.47
   245.3 3111.08   249.6 3112.12   262.4 3121.79   272.4 3130.19   296.4 3151.95
   311.6    3164   323.3 3172.04   330.5 3175.29   334.7 3175.94   402.1 3175.66
#Mann= 3 ,-1,0
       0      .1       0  148.79    .045       0  169.85      .1       0
Bank Sta=148.79,169.85
XS Rating Curve= 0 ,0
Exp/Cntr=0.3,0.1

Type RM Length L Ch R = 1 ,13148   ,412.8,417,418.8
XS GIS Cut Line= 2
2430550.97148846715412.7773128942430771.29096888715847.487112408
#Sta/Elev= 30
       0 3159.68    10.1 3158.85      22 3156.12    45.3    3153    66.7  3141.6
    81.5 3131.49    99.1 3121.97     117 3118.69     126 3118.85   130.5 3117.74
   148.4 3106.45   152.9 3104.36   170.8 3101.92   179.8 3097.03   209.5 3095.65
   215.5 3092.63   220.2 3088.61  225.54 3086.17   232.7 3085.76   243.7 3086.16
   287.5  3089.6   300.9 3091.84   327.8 3091.19   341.3 3092.33   350.2 3096.17
   368.2 3106.82   409.7 3134.98   444.6 3154.22   453.4 3156.82   487.4 3157.09
#Mann= 3 ,-1,0
       0      .1       0  225.54    .045       0   243.7      .1       0
Bank Sta=225.54,243.7
XS Rating Curve= 0 ,0
Exp/Cntr=0.3,0.1

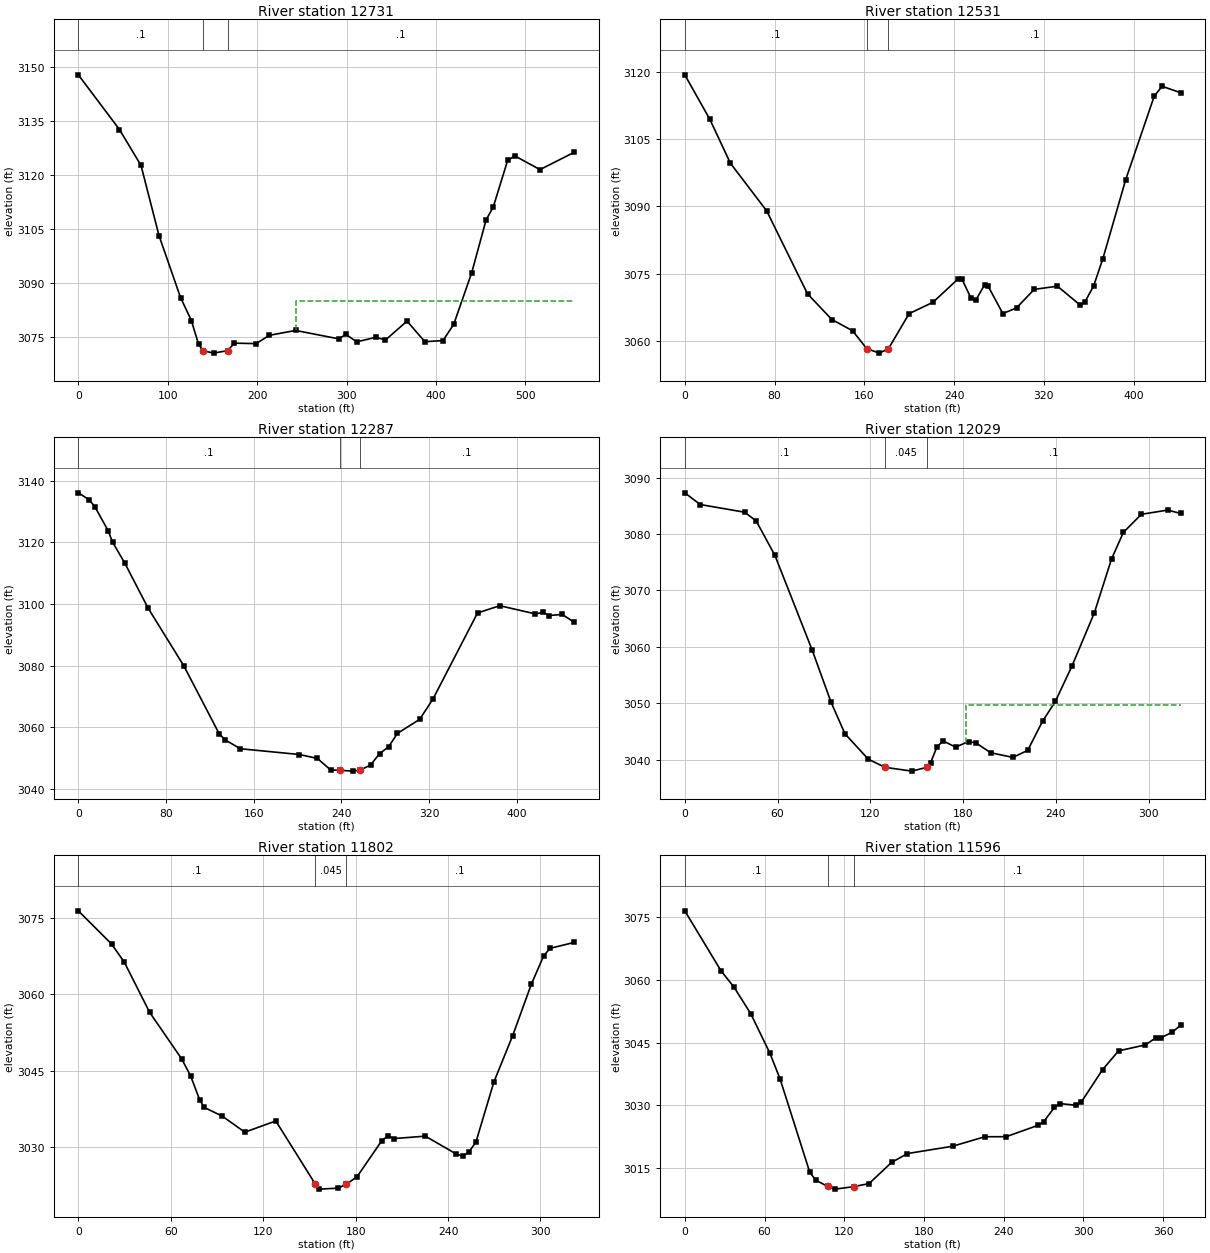
Type RM Length L Ch R = 1 ,12731   ,206,200.6,189.5
XS GIS Cut Line= 2
2430297.82305083715519.4206535332430352.91156237716071.202531127
#Sta/Elev= 30
       0 3147.89      46 3132.68    70.1 3122.69    90.2  3103.2   114.3 3085.95
   126.4 3079.56   134.4 3073.01  139.333071.184   151.2 3070.49  166.863071.183
   174.6 3073.27   198.7 3073.13   213.7 3075.44     243  3076.8   291.2 3074.46
   299.2  3075.7   311.3 3073.63   332.7 3074.89   343.5 3074.14   367.6  3079.4
   387.5 3073.67   407.8 3073.98   419.8 3078.49   439.9 3092.83     456 3107.52
   464.1 3111.19   480.1 3124.08   488.2 3125.34   516.3 3121.53   554.5 3126.33
#Mann= 3 ,-1,0
       0      .1       0  139.33    .045       0  166.86      .1       0
#XS Ineff= 2 , 0
                          242.93            3085
Permanent Ineff=
       F       F
Bank Sta=139.33,166.86
XS Rating Curve= 0 ,0
Exp/Cntr=0.3,0.1

Type RM Length L Ch R = 1 ,12531   ,238,243.3,248.4
XS GIS Cut Line= 4
2430106.61907691715625.0936189322430126.25395322715748.793339741
 2430204.7934585715839.1137708072430237.19100443716033.499046364
#Sta/Elev= 30
       0 3119.37    22.4 3109.41    40.6 3099.67      73 3089.02   109.4 3070.51
   131.1 3064.79   149.6 3062.27  162.213058.283   173.5 3057.29  181.583058.284
     200 3066.11   221.2 3068.62   243.1 3073.72     247 3073.83   255.1 3069.57
   259.2 3069.03   267.3 3072.53   270.5 3072.17   283.5 3066.12   295.7 3067.38
   311.5 3071.51   332.2 3072.22   352.5    3068   356.5 3068.63   364.4 3072.25
   372.7 3078.37     393 3095.95   418.5 3114.63   425.5 3116.81     442 3115.38
#Mann= 3 ,-1,0
       0      .1       0  162.21    .045       0  181.58      .1       0
Bank Sta=162.21,181.58
XS Rating Curve= 0 ,0
Exp/Cntr(USF)=0,0
Exp/Cntr=0.3,0.1

Type RM Length L Ch R = 1 ,12287   ,257.2,258.1,258.6
XS GIS Cut Line= 2
 2429895.6290965715630.3973137212429974.01373278716076.096533119
#Sta/Elev= 30
       0 3136.11     9.8 3133.88      15 3131.67    27.1 3123.88    31.3 3120.06
    42.2 3113.44    63.7 3098.69    96.4  3079.9   128.7 3057.85   134.1 3055.94
   147.9 3053.09   201.8 3051.22   218.1 3049.96   230.3  3046.2   238.4 3046.11
   250.6 3045.83   257.2 3046.13   266.8 3047.86   274.9  3051.5   283.1  3053.7
   291.2 3058.07   311.5 3062.62   323.7 3069.26   364.3 3097.14   384.6 3099.49
   417.1 3096.84   424.3 3097.36   429.3  3096.3   441.5 3096.66   452.5 3094.15
#Mann= 3 ,-1,0
       0      .1       0   238.4    .045       0   257.2      .1       0
Bank Sta=238.4,257.2
XS Rating Curve= 0 ,0
Exp/Cntr=0.3,0.1

Type RM Length L Ch R = 1 ,12029   ,226.7,227.1,225.6
XS GIS Cut Line= 3
 2429667.2094548715771.2769392492429688.07418148715951.370347195
2429764.74956232716067.810473335
#Sta/Elev= 30
       0 3087.33      10 3085.25    38.7 3083.89    46.2 3082.33    58.3 3076.22
    82.4 3059.42    94.5 3050.24   103.6 3044.56   118.7 3040.06  129.493038.615
   146.9 3037.94  156.513038.616     159 3039.44     163 3042.18     167 3043.31
   175.1 3042.21   183.5 3043.18   188.3 3042.95   197.8 3041.21   212.2 3040.37
   221.8 3041.63   231.4 3046.79   239.7 3050.32   250.5 3056.64   264.9 3066.04
     276 3075.59   283.7 3080.32   295.3 3083.52   312.4 3084.27   320.7 3083.67
#Mann= 3 ,-1,0
       0      .1       0  129.49    .045       0  156.51      .1       0
#XS Ineff= 2 , 0
                          182.11         3049.73
Permanent Ineff=
       F       F
Bank Sta=129.49,156.51
XS Rating Curve= 0 ,0
Exp/Cntr(USF)=0,0
Exp/Cntr=0.3,0.1

Type RM Length L Ch R = 1 ,11802   ,191.2,205.9,209.1
XS GIS Cut Line= 3
2429518.69385978715808.590198577 2429459.0529841715915.585785104
2429489.57301043716112.614371957
#Sta/Elev= 30
       0 3076.38    21.6 3069.85    29.8 3066.31    46.3 3056.43      67 3047.33
    72.9 3043.94    78.7 3039.29    81.7 3037.75    93.4 3036.04   108.1 3032.88
   128.2 3035.09  153.973022.623   156.5 3021.69   168.6 3021.88  173.873022.625
     181 3024.14     197  3031.2     201 3032.14   205.1 3031.63   225.3  3032.1
   245.5 3028.56   249.6 3028.17   253.6 3029.01   258.1 3030.92   269.8 3042.76
     282 3051.86   294.1 3061.96   302.2 3067.59   306.3 3069.01   321.9 3070.17
#Mann= 3 ,-1,0
       0      .1       0  153.97    .045       0  173.87      .1       0
Bank Sta=153.97,173.87
XS Rating Curve= 0 ,0
Exp/Cntr=0.3,0.1

Type RM Length L Ch R = 1 ,11596   ,145,139.1,128.3
XS GIS Cut Line= 3
2429440.76309681715717.5778748672429317.50516072715844.811873413
2429295.23921097716039.638933686
#Sta/Elev= 30
       0 3076.54    27.3 3062.15    36.9 3058.32    49.6 3051.92    64.1 3042.41
    71.8 3036.19    94.1 3013.88    98.6 3012.03   107.6 3010.51   113.3 3009.88
   127.4 3010.49   138.7 3011.21   155.7 3016.29   167.6  3018.4   201.7 3020.16
   225.8 3022.43   241.9 3022.44   266.1 3025.19   270.1 3026.01   278.2 3029.45
   282.2 3030.38   294.3 3029.97   298.3 3030.67   314.4 3038.48   326.5    3043
   346.6 3044.42   354.7 3046.15   358.7 3046.17     367  3047.5   373.2 3049.12
#Mann= 3 ,-1,0
       0      .1       0   107.6    .045       0   127.4      .1       0
Bank Sta=107.6,127.4
XS Rating Curve= 0 ,0
Exp/Cntr(USF)=0,0
Exp/Cntr=0.3,0.1

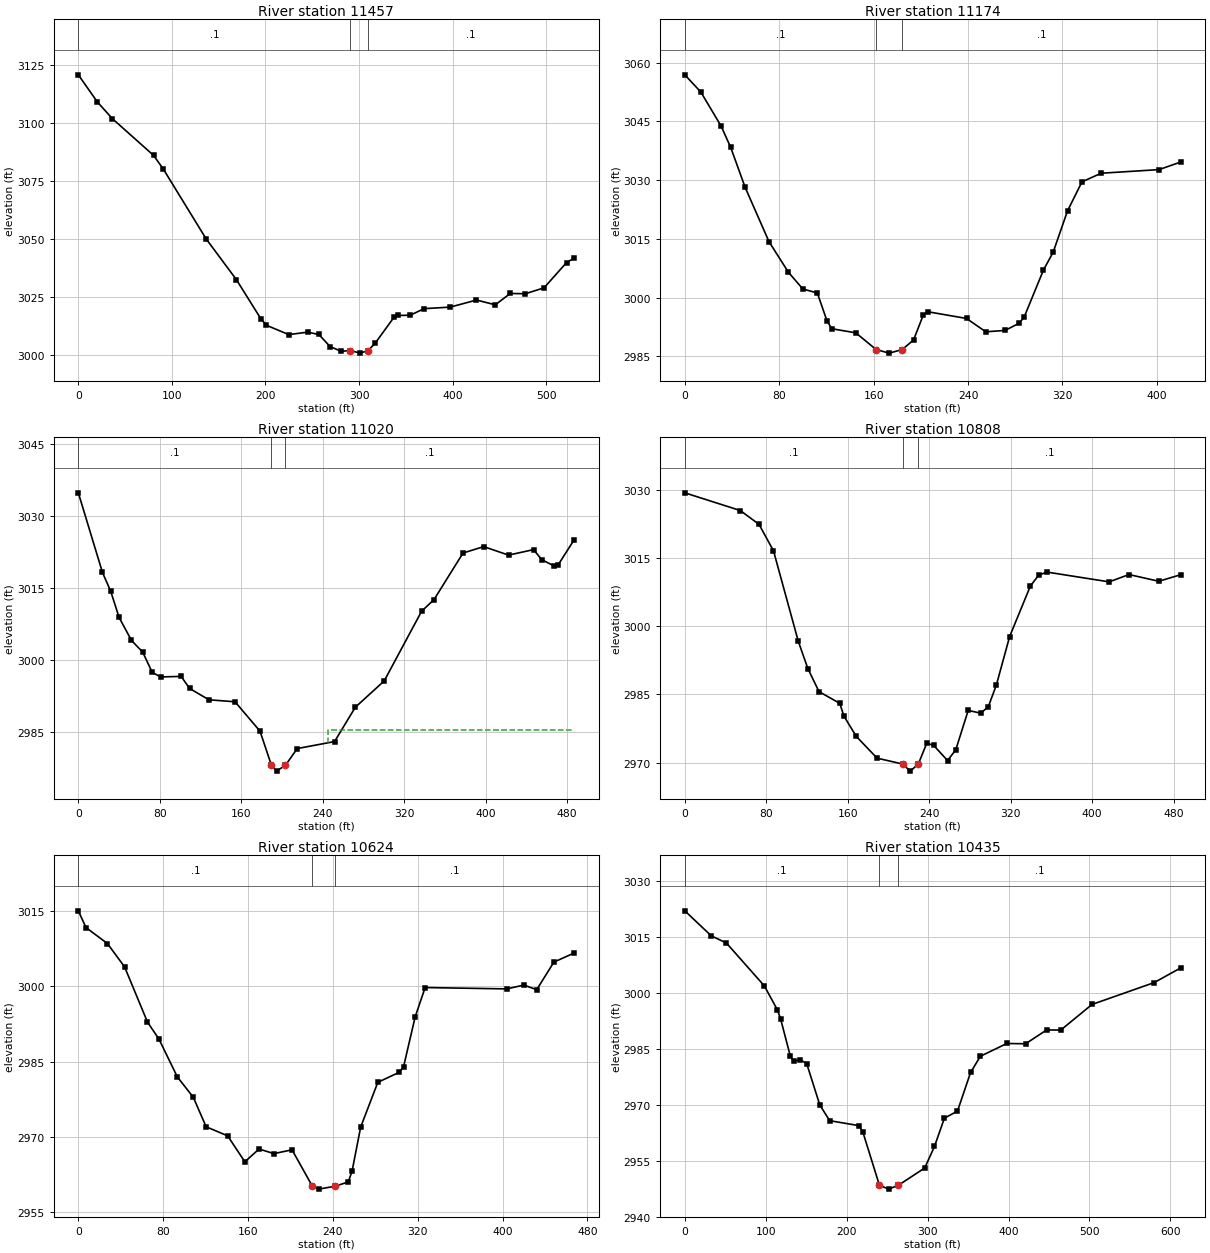
Type RM Length L Ch R = 1 ,11457   ,281.2,283.3,280
XS GIS Cut Line= 2
2429214.48297226715452.9315103752429256.77410934715981.283646963
#Sta/Elev= 30
       0 3120.93    20.3 3109.26    36.4 3102.03    80.5 3086.18      91 3080.21
   136.7 3050.18     169 3032.64     195 3015.87   200.9 3013.03     225 3008.98
     245 3010.04   257.1 3009.03   269.1 3003.83   281.1 3001.77   290.7 3002.12
   301.2    3001  309.813002.107   317.3 3005.28   337.3 3016.39   341.3 3017.22
   354.8 3017.34   369.6 3020.17   397.5 3020.83   425.6 3023.88   445.7 3021.82
   461.7 3026.71   477.8 3026.59   497.8 3029.14   521.9 3040.04     530 3041.93
#Mann= 3 ,-1,0
       0      .1       0   290.7    .045       0  309.81      .1       0
Bank Sta=290.7,309.81
XS Rating Curve= 0 ,0
Exp/Cntr=0.3,0.1

Type RM Length L Ch R = 1 ,11174   ,154.5,153.9,153.6
XS GIS Cut Line= 2
2428966.34655994 715683.037279832429047.77499757716095.164882535
#Sta/Elev= 30
       0 3056.89    13.6 3052.49    30.7 3043.84    38.9 3038.35    51.1 3028.18
    71.3 3014.32    87.8 3006.48     100 3002.22   112.3 3001.19   120.4 2994.13
   124.5 2992.07   144.9 2991.02  162.142986.747   173.2 2985.84   184.12986.746
   193.8 2989.18     202 2995.52     206  2996.4   238.7 2994.69     255 2991.29
   271.3 2991.63   283.5  2993.5   287.6  2995.1   303.9 3007.07   312.1 3011.61
   324.3 3022.18   336.5 3029.56   352.8 3031.77   401.8 3032.69   420.1 3034.62
#Mann= 3 ,-1,0
       0      .1       0  162.14    .045       0   184.1      .1       0
Bank Sta=162.14,184.1
XS Rating Curve= 0 ,0
Exp/Cntr(USF)=0,0
Exp/Cntr=0.3,0.1

Type RM Length L Ch R = 1 ,11020   ,212.2,212.3,212.2
XS GIS Cut Line= 2
2428817.76428374715701.8795666162428907.50174562716180.479363306
#Sta/Elev= 30
       0 3034.77    23.7 3018.22    31.8 3014.32      40 3008.89    52.2  3004.1
    63.2 3001.68    72.5 2997.49    80.7 2996.52     101 2996.63   109.2 2994.13
   128.3 2991.77   153.9 2991.36   178.4 2985.25  189.63 2978.16   194.6 2976.95
  203.342978.158     215 2981.64   251.6 2983.09     272 2990.22   300.4  2995.7
   337.1 3010.17   349.3 3012.59   377.8 3022.27   398.1 3023.59   422.5 3021.83
     447 3022.97   455.1 3020.88   467.3 3019.56   471.4 3019.87   486.9 3025.03
#Mann= 3 ,-1,0
       0      .1       0  189.63    .045       0  203.34      .1       0
#XS Ineff= 2 , 0
                          244.91         2985.51
Permanent Ineff=
       F       F
Bank Sta=189.63,203.34
XS Rating Curve= 0 ,0
Exp/Cntr(USF)=0,0
Exp/Cntr=0.3,0.1

Type RM Length L Ch R = 1 ,10808   ,180.9,183.4,183.8
XS GIS Cut Line= 2
2428604.62858239715711.6185100332428694.36604427716190.218306723
#Sta/Elev= 30
       0  3029.4    54.5  3025.5    72.9 3022.45    87.1 3016.62   111.5 2996.66
   120.9 2990.66   131.8 2985.61   152.2 2983.03   156.2 2980.24   168.4 2975.75
   188.8 2970.96   213.92969.665   221.4  2968.1  229.342969.665   237.6 2974.25
   244.3 2973.79     258 2970.44   266.1 2972.79   278.3 2981.48   290.5 2980.87
     298 2982.26     306  2987.1     319 2997.75   339.4 3008.89   347.5 3011.26
   355.7 3011.94   416.7 3009.79   436.2  3011.4   465.5 3009.92   486.9 3011.36
#Mann= 3 ,-1,0
       0      .1       0   213.9    .045       0  229.34      .1       0
Bank Sta=213.9,229.34
XS Rating Curve= 0 ,0
Exp/Cntr(USF)=0,0
Exp/Cntr=0.3,0.1

Type RM Length L Ch R = 1 ,10624   ,189.5,189.6,188.9
XS GIS Cut Line= 2
2428452.84886141715786.0691805062428524.30646994  716248.0509287
#Sta/Elev= 30
       0 3015.01     7.2 3011.68    27.4  3008.5    43.6 3003.85    65.2 2992.85
      76 2989.47    93.3 2981.95   108.4 2977.87   120.5    2972   140.8 2970.19
     157 2965.02   170.4 2967.57   184.4 2966.65   201.5 2967.41  220.72 2960.14
   226.5 2959.58     242 2960.15   254.5 2961.01   258.1 2963.16   266.2 2971.93
   282.4 2980.86   302.7 2982.86   306.7    2984   317.6  2993.9     327 2999.73
   403.9 2999.46     420 3000.22   432.2 2999.31   448.4  3004.8   467.5 3006.61
#Mann= 3 ,-1,0
       0      .1       0  220.72    .045       0     242      .1       0
Bank Sta=220.72,242
XS Rating Curve= 0 ,0
Exp/Cntr(USF)=0,0
Exp/Cntr=0.3,0.1

Type RM Length L Ch R = 1 ,10435   ,286.2,282.3,279
XS GIS Cut Line= 4
2428297.29151174715739.1282249732428286.72805171715875.857772697
 2428326.6184467 716130.675512842428445.48834317 716312.90825505
#Sta/Elev= 30
       0 3021.96    32.7 3015.26    51.4 3013.33    98.3 3001.83   114.4 2995.41
   118.4 2992.97   130.4 2982.99   134.5 2981.59   142.5 2982.03   150.6 2981.02
   166.8 2969.92     179 2965.71   215.4 2964.37   220.1 2962.59  240.432948.414
   251.8 2947.36  264.032948.414   296.4 2953.02   308.5  2958.8   320.7 2966.37
   336.9 2968.28   353.1 2978.63   365.2 2982.98   397.9  2986.4   421.1 2986.32
   447.1 2990.04   464.5 2989.99   503.1 2996.86   580.1 3002.74   612.6 3006.65
#Mann= 3 ,-1,0
       0      .1       0  240.43    .045       0  264.03      .1       0
Bank Sta=240.43,264.03
XS Rating Curve= 0 ,0
Exp/Cntr=0.3,0.1

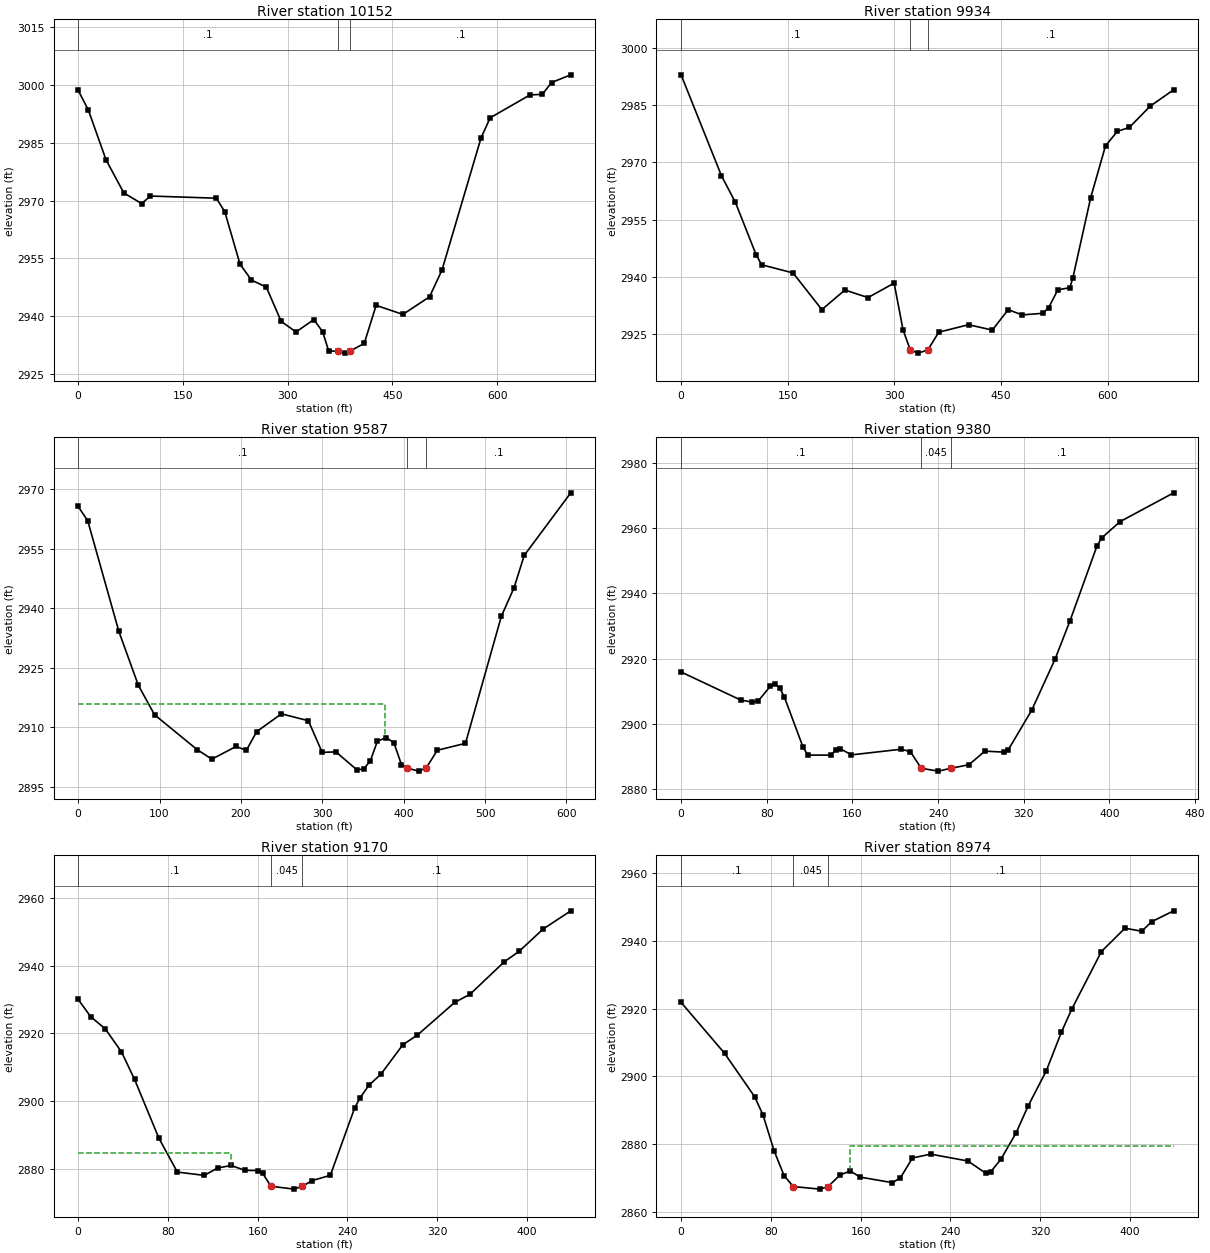
Type RM Length L Ch R = 1 ,10152   ,217.4,218.1,216.1
XS GIS Cut Line= 3
2427969.26365017715807.6726435512428145.41496423716297.905074188
2428313.25725404716374.348097271
#Sta/Elev= 30
       0 2998.56    14.4 2993.52    39.9 2980.55    65.4 2971.95    90.9 2969.21
   103.5 2971.16   197.9  2970.6   209.9 2967.09   231.7 2953.52   248.1 2949.38
   269.4 2947.56   290.6 2938.69   311.9 2935.93   337.4 2939.13   350.1 2935.99
   358.6 2931.02   371.4 2930.95   381.8 2930.45   389.1 2930.95   409.6 2932.97
   426.6 2942.83   464.9 2940.48   503.1 2945.05   520.9 2951.97   576.8 2986.21
   589.9 2991.44     647 2997.37   664.6 2997.51   677.8 3000.58   705.3 3002.57
#Mann= 3 ,-1,0
       0      .1       0   371.4    .045       0   389.1      .1       0
Bank Sta=371.4,389.1
XS Rating Curve= 0 ,0
Exp/Cntr(USF)=0,0
Exp/Cntr=0.3,0.1

Type RM Length L Ch R = 1 ,9934    ,344.2,347,342.4
XS GIS Cut Line= 3
 2427830.3915133 715849.840968532427877.40985691716138.394321492
2427995.62601779716520.639149388
#Sta/Elev= 30
       0    2993    56.7 2966.53    76.3 2959.55   105.5 2945.75   113.2 2943.14
   157.4 2940.99   197.9 2931.36   230.3 2936.51   262.8 2934.52   299.5 2938.32
     312 2926.08  322.25 2920.75     333 2919.94  346.792920.749   362.3 2925.44
   404.1  2927.4   437.5 2925.99   459.9 2931.35   479.5 2929.97   508.8  2930.4
   516.7 2931.89   529.7 2936.56   546.5 2937.12   550.7 2939.63   575.8 2960.73
   596.7 2974.39   613.4 2978.16   630.2  2979.2   659.5 2984.78   692.5 2989.08
#Mann= 3 ,-1,0
       0      .1       0  322.25    .045       0  346.79      .1       0
Bank Sta=322.25,346.79
XS Rating Curve= 0 ,0
Exp/Cntr(USF)=0,0
Exp/Cntr=0.3,0.1

Type RM Length L Ch R = 1 ,9587    ,208.6,207.4,206.7
XS GIS Cut Line= 2
  2427509.269296715985.9977918142427708.46207893716557.684194955
#Sta/Elev= 30
       0  2965.6    11.8 2961.97      50 2934.17    73.9 2920.62    93.9 2913.18
   146.1 2904.44   164.3 2902.02     194 2905.21   206.7 2904.24   219.4 2908.95
   249.8 2913.43   282.9 2911.69   299.9 2903.73   316.8 2903.85   342.2  2899.4
   350.7 2899.48   359.2 2901.65   367.7 2906.54   378.6 2907.43     388 2906.17
   397.3 2900.66   403.7 2899.81   418.5 2899.01  427.842899.837   441.4 2904.26
     476    2906   520.1 2937.98   535.7 2945.16   548.2 2953.28   605.4 2969.03
#Mann= 3 ,-1,0
       0      .1       0   403.7    .045       0  427.84      .1       0
#XS Ineff= 2 , 0
          376.75 2915.79
Permanent Ineff=
       F       F
Bank Sta=403.7,427.84
XS Rating Curve= 0 ,0
Exp/Cntr=0.3,0.1

Type RM Length L Ch R = 1 ,9380    ,203.5,210.3,213.6
XS GIS Cut Line= 2
2427355.75615639 716224.522743872427537.52184282716647.133479248
#Sta/Elev= 30
       0 2915.87    55.6 2907.26      66 2906.64    71.9 2906.92    83.4 2911.53
    87.8 2912.21    92.2 2910.91    96.5 2908.12   113.9 2892.78   118.3 2890.34
   140.1 2890.34   144.4 2891.93   148.8 2892.27   159.1 2890.41   205.4 2892.14
   214.1 2891.41  224.27 2886.28   240.2 2885.42  251.77 2886.28   268.8 2887.39
   283.7 2891.56   301.2 2891.26   305.5 2891.95   327.3 2904.06   349.1 2919.71
   363.1 2931.51   388.2 2954.42   392.6 2956.99     410 2962.06     460 2970.89
#Mann= 3 ,-1,0
       0      .1       0  224.27    .045       0  251.77      .1       0
Bank Sta=224.27,251.77
XS Rating Curve= 0 ,0
Exp/Cntr=0.3,0.1

Type RM Length L Ch R = 1 ,9170    ,202.9,195.6,190.2
XS GIS Cut Line= 4
 2427215.7111503716274.9562281562427245.62363759 716344.75203184
2427252.27085699716489.3290537572427333.69929462 716692.06924541
#Sta/Elev= 30
       0 2930.01    11.2  2924.9    24.2 2921.29    38.6 2914.51    50.3 2906.36
      72 2888.99    88.4 2879.02   112.4 2878.04   124.4 2880.22   136.4 2880.97
   148.4 2879.54   160.5 2879.46   164.5 2878.64  171.782874.838   192.5 2873.98
  199.882874.841   208.5 2876.48   224.8 2878.07   246.4 2897.91   251.2  2900.9
   259.3 2904.72   269.7 2907.85   289.5 2916.66   302.4 2919.47   335.8 2929.17
   349.2 2931.49     380 2941.17   392.9 2944.16   414.5  2950.8   439.1 2956.17
#Mann= 3 ,-1,0
       0      .1       0  171.78    .045       0  199.88      .1       0
#XS Ineff= 2 , 0
          136.59 2884.74
Permanent Ineff=
       F       F
Bank Sta=171.78,199.88
XS Rating Curve= 0 ,0
Exp/Cntr(USF)=0,0
Exp/Cntr=0.3,0.1

Type RM Length L Ch R = 1 ,8974    ,278.9,278.1,277.7
XS GIS Cut Line= 2
2427003.32775053716366.657680112 2427200.9703868716758.595337142
#Sta/Elev= 30
       0  2921.8    38.7 2906.81    65.5    2894      73  2888.6    82.9 2878.01
    91.8 2870.68     1002867.458   123.8  2866.7  130.942867.459   141.7 2870.87
   150.7 2872.05   159.6 2870.25   188.4  2868.6   195.5 2870.05   206.2 2875.89
   222.3 2877.03   255.6    2875   271.6 2871.37   276.1 2871.86   285.1 2875.56
   298.5 2883.25   309.2 2891.19   325.4 2901.56     339 2913.08   348.3  2919.9
   374.6 2936.82   395.6  2943.7   410.5 2942.81   419.4 2945.63     439 2948.83
#Mann= 3 ,-1,0
       0      .1       0     100    .045       0  130.94      .1       0
#XS Ineff= 2 , 0
                          150.41         2879.49
Permanent Ineff=
       F       F
Bank Sta=100,130.94
XS Rating Curve= 0 ,0
Exp/Cntr=0.3,0.1

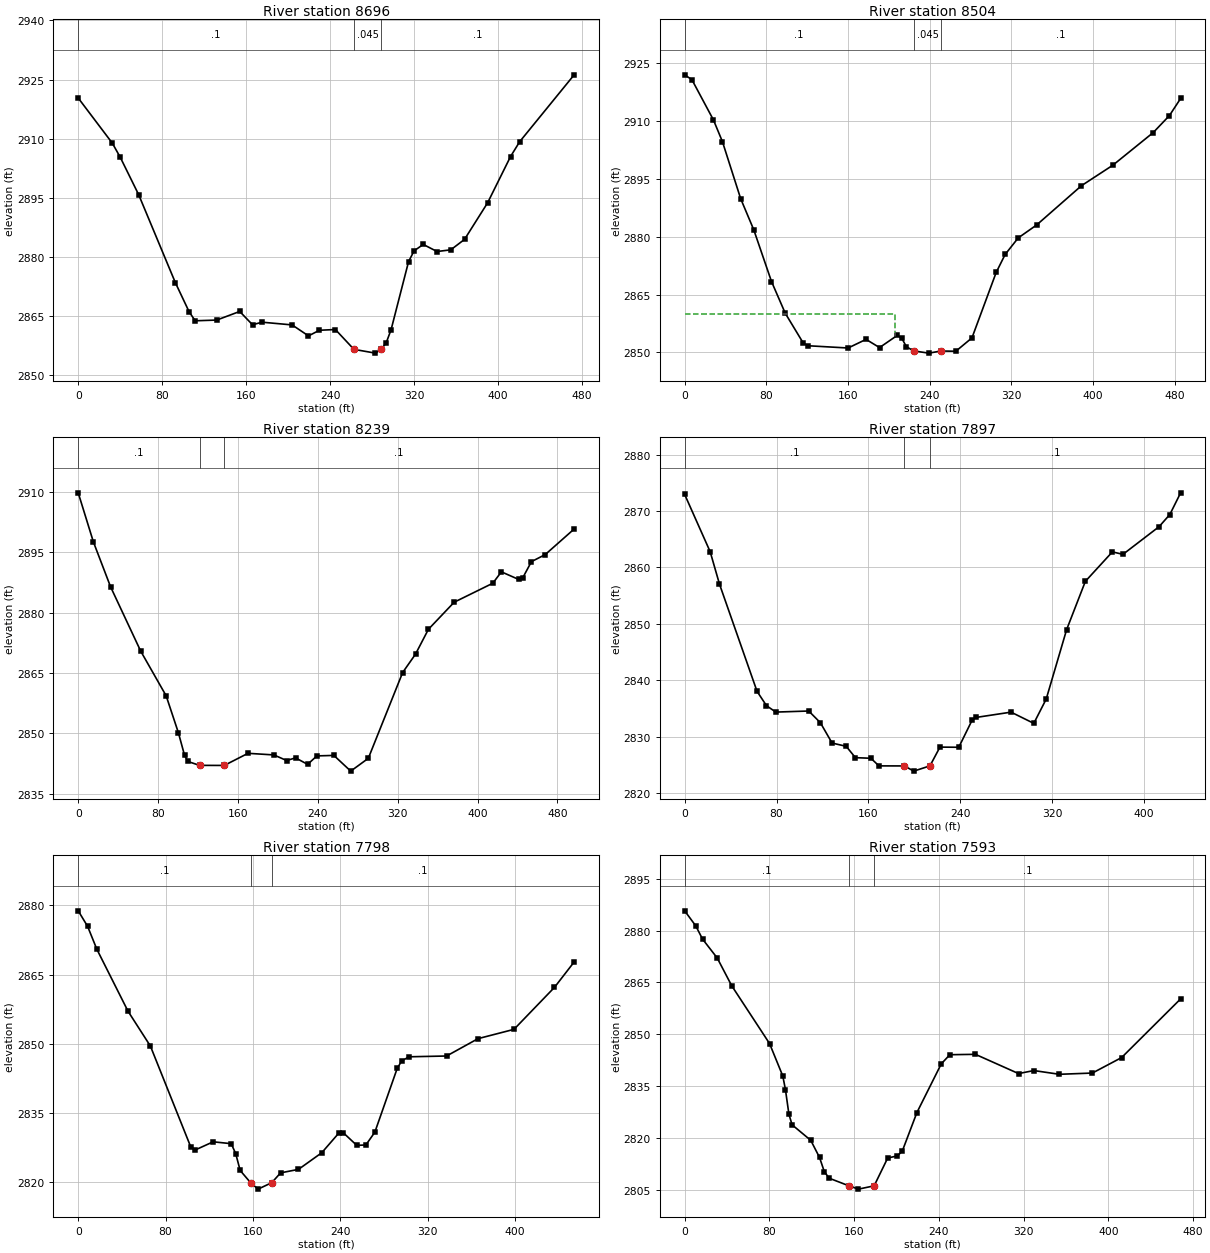
Type RM Length L Ch R = 1 ,8696    ,192.8,191.9,192.4
XS GIS Cut Line= 2
 2426786.0060935716432.5096801132426976.55804267716864.716339474
#Sta/Elev= 30
       0  2920.3    32.5 2908.82    40.1  2905.2    57.6 2895.72    92.5 2873.39
   105.6 2865.99   111.4 2863.69   131.9 2863.87   153.8 2866.06     166 2862.68
   175.1 2863.33   203.7 2862.64   219.3 2859.85   229.7 2861.28   244.9 2861.47
  262.572856.429     283 2855.47  288.692856.427   293.4 2858.16     298 2861.46
   314.6 2878.72   319.9 2881.47   328.6 2883.09   341.7 2881.29   354.8 2881.72
   367.9 2884.37   389.8 2893.63   411.7 2905.41   420.4 2909.19   472.3 2926.19
#Mann= 3 ,-1,0
       0      .1       0  262.57    .045       0  288.69      .1       0
Bank Sta=262.57,288.69
XS Rating Curve= 0 ,0
Exp/Cntr=0.3,0.1

Type RM Length L Ch R = 1 ,8504    ,260.5,265.2,262.9
XS GIS Cut Line= 2
2426613.24052942716503.5451820172426814.31891622716945.585272016
#Sta/Elev= 30
       0 2922.05     7.1 2920.78    28.2 2910.32      37 2904.68    54.8 2889.92
    67.7 2881.79      85  2868.4    98.5 2860.15     116 2852.47   120.4 2851.73
     160 2851.14   177.6 2853.38   190.8 2851.25   208.3 2854.44   212.7 2853.61
   217.1 2851.46  224.32 2850.38     239 2849.81   251.1 2850.36   265.5  2850.3
   281.3 2853.77     305 2870.75   313.8 2875.43   326.6 2879.72   344.6 2883.07
   388.5 2893.27   419.3  2898.6   458.8 2907.07   474.6 2911.46   485.6 2915.91
#Mann= 3 ,-1,0
       0      .1       0  224.32    .045       0   251.1      .1       0
#XS Ineff= 2 , 0
        205.7104    2860
Permanent Ineff=
       T       F
Bank Sta=224.32,251.1
XS Rating Curve= 0 ,0
Exp/Cntr(USF)=0,0
Exp/Cntr=0.3,0.1

Type RM Length L Ch R = 1 ,8239    ,341.2,341.8,343.2
XS GIS Cut Line= 2
2426408.07399339716599.0081738312426590.87252684717060.989922025
#Sta/Elev= 30
       0 2909.73    15.2 2897.55    32.4 2886.41    62.6 2870.44    88.1 2859.35
   100.4 2850.15   106.5  2844.6   109.9 2843.05  121.542842.091   146.3 2842.07
   170.1 2845.08     196 2844.68   208.8 2843.29   217.7 2843.95   229.8 2842.34
   239.1 2844.44   256.1 2844.56     273 2840.66   290.6 2843.84     325 2865.13
   337.9  2869.7   350.8 2875.86   376.6 2882.58   415.3 2887.29   423.9 2890.12
   441.1 2888.25   445.4 2888.68     454 2892.65   467.8  2894.4   496.8 2900.75
#Mann= 3 ,-1,0
       0      .1       0  121.54    .045       0   146.3      .1       0
Bank Sta=121.54,146.3
XS Rating Curve= 0 ,0
Exp/Cntr(USF)=0,0
Exp/Cntr=0.3,0.1

Type RM Length L Ch R = 1 ,7897    ,101.4,99.2,101.7
XS GIS Cut Line= 2
 2426198.5113804716775.4732968722426285.11002066717198.446820788
#Sta/Elev= 30
       0 2872.95    22.2 2862.79    30.3 2857.05      63 2838.03    71.2  2835.5
    79.3 2834.36     108 2834.55   118.1 2832.48   128.3 2828.87   140.6 2828.29
   148.6 2826.28   162.1 2826.17   169.1 2824.82  191.32 2824.81   199.4 2823.89
  213.522824.823   222.2 2828.15   238.6 2828.12   250.3 2832.97   253.6 2833.41
   284.1 2834.35   303.9 2832.36   314.7 2836.67   332.5    2849   348.8 2857.55
   372.3 2862.77   381.5 2862.33   412.9 2867.23   422.3 2869.39   431.7 2873.24
#Mann= 3 ,-1,0
       0      .1       0  191.32    .045       0  213.52      .1       0
Bank Sta=191.32,213.52
XS Rating Curve= 0 ,0
Exp/Cntr(USF)=0,0
Exp/Cntr=0.3,0.1

Type RM Length L Ch R = 1 ,7798    ,207.6,204.6,201.4
XS GIS Cut Line= 2
2426100.26548286716800.8323027432426204.40482494717242.798611383
#Sta/Elev= 30
       0 2878.83     8.6 2875.47      17 2870.54    45.6 2857.09    66.1 2849.54
   103.1 2827.67   107.2 2827.05   123.6 2828.81   140.1  2828.4   144.2 2826.25
   148.3  2822.6  157.832819.959   164.7 2818.56  177.242819.959   185.3 2822.08
   201.7 2822.84     223 2826.44   238.7 2830.72   242.8 2830.75   255.1 2828.03
   263.4 2828.13   271.6 2830.89   292.1 2844.72   296.2 2846.32   302.9 2847.22
   337.3 2847.39   366.1 2851.15     399 2853.16   436.1 2862.26   454.1 2867.76
#Mann= 3 ,-1,0
       0      .1       0  157.83    .045       0  177.24      .1       0
Bank Sta=157.83,177.24
XS Rating Curve= 0 ,0
Exp/Cntr=0.3,0.1

Type RM Length L Ch R = 1 ,7593    ,203.6,199.6,193.9
XS GIS Cut Line= 2
2425864.66380756716886.5004128152426095.65468166717293.642600972
#Sta/Elev= 30
       0 2885.74    10.4 2881.41    16.9 2877.54    30.7 2872.09    44.5 2863.99
    80.1 2847.32    92.6 2837.92    95.1 2833.99    98.4 2826.82   101.4 2823.78
     119 2819.29   127.3 2814.32   131.8 2810.21   136.4 2808.32  155.052806.115
     164 2805.16  178.832806.114   191.6 2814.16   200.8 2814.79   205.4 2816.18
   219.2 2827.34   242.2 2841.44   250.3 2844.08   274.4 2844.19   315.1 2838.62
   329.6 2839.49   353.7 2838.41   384.8 2838.77   412.4 2843.25   468.1 2860.24
#Mann= 3 ,-1,0
       0      .1       0  155.05    .045       0  178.83      .1       0
Bank Sta=155.05,178.83
XS Rating Curve= 0 ,0
Exp/Cntr(USF)=0,0
Exp/Cntr=0.3,0.1