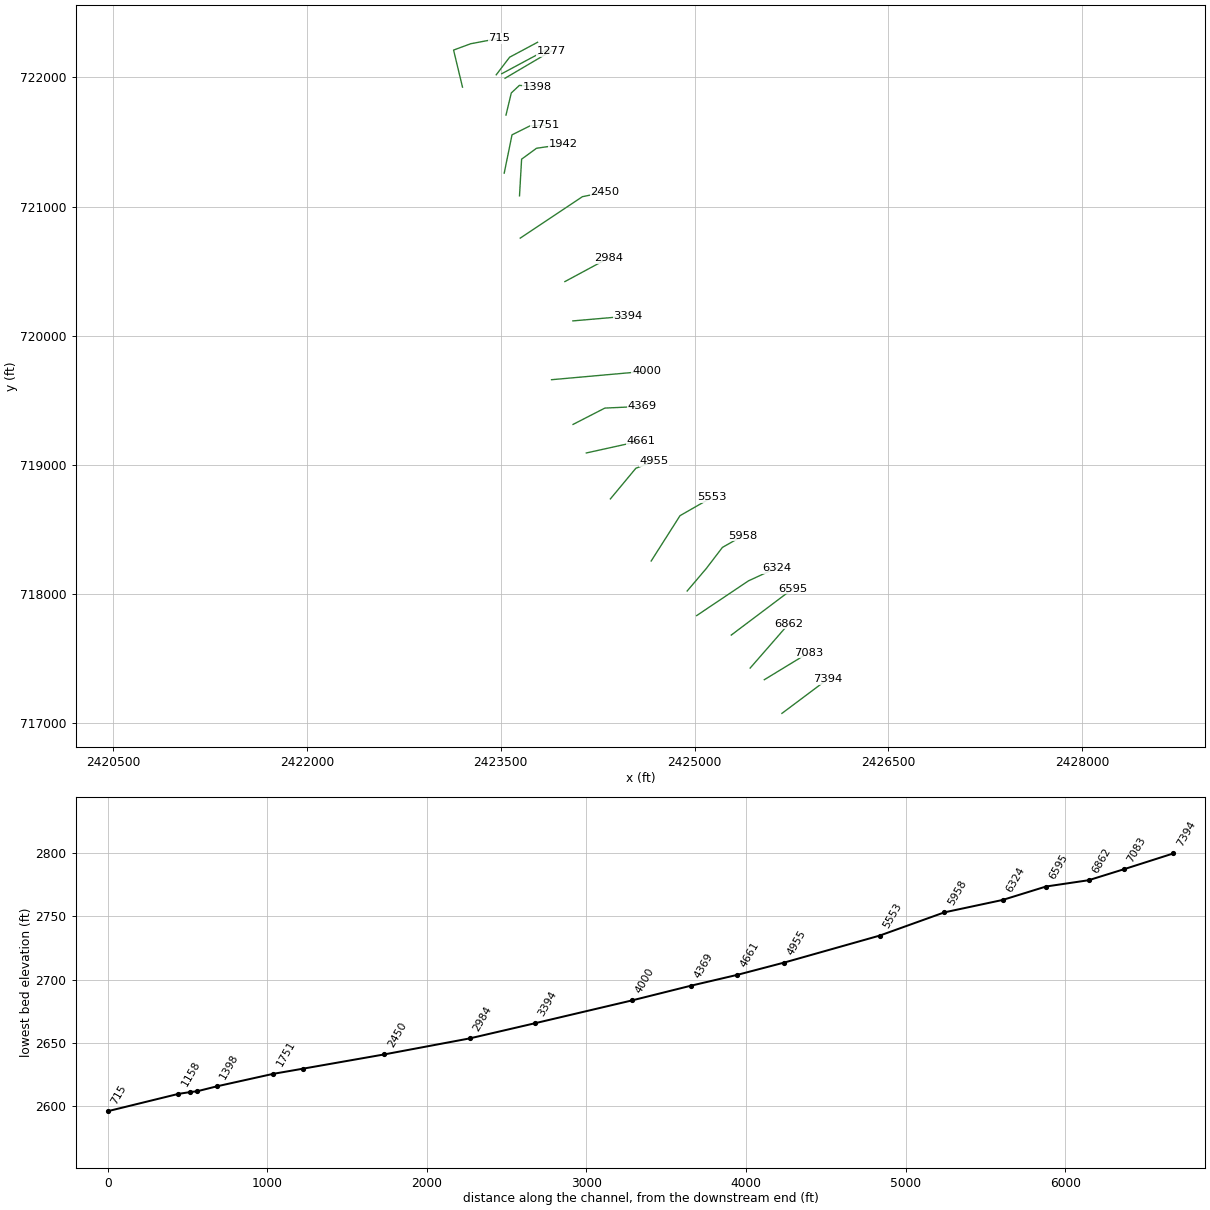
HEC-RAS study SFKREDCK.prj: SFKREDCK

--- SFKREDCK.g01 (geometry) --- (continued)

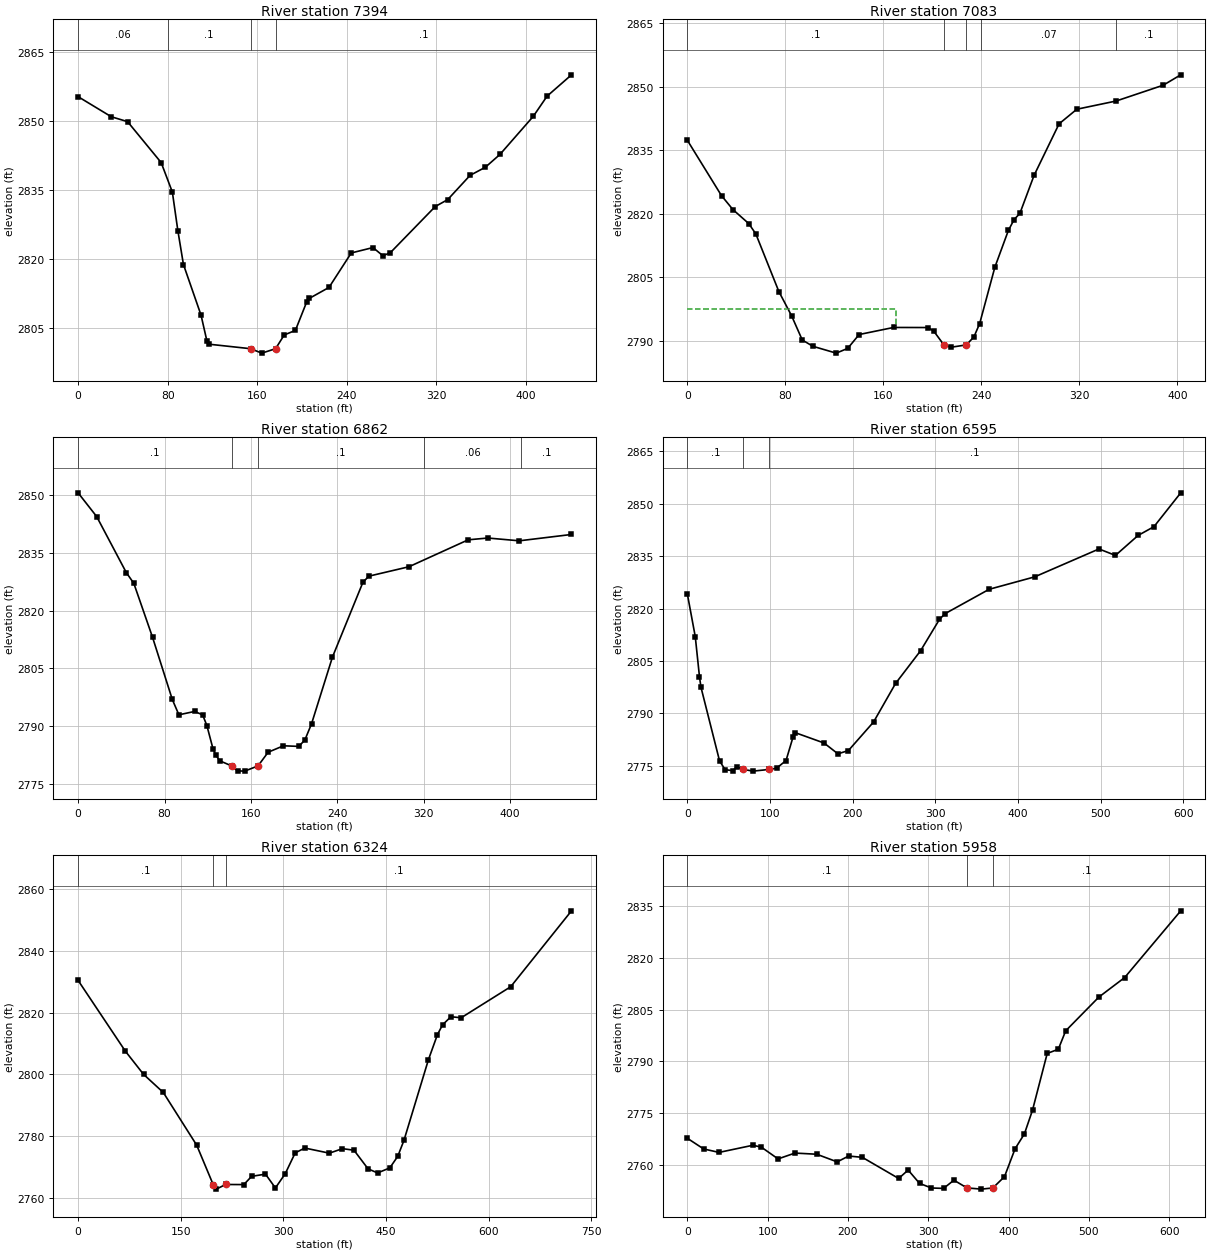
Type RM Length L Ch R = 1 ,7394    ,308.7,310.8,306.6
XS GIS Cut Line= 2
2425676.80476424717075.366427191  2426029.617205717339.449266404
#Sta/Elev= 30
       0 2855.29    29.7 2850.92    44.2 2849.86    74.2 2840.97    84.2 2834.56
    89.1  2826.2    94.1 2818.83   109.8 2807.84   115.1 2802.18   116.5 2801.53
   154.1 2800.54   164.1 2799.58  176.39 2800.54   184.1 2803.52   194.1 2804.52
   204.1 2810.65   206.6 2811.48   224.1 2813.85     244 2821.34   263.4 2822.51
   272.3 2820.72     279 2821.42     319 2831.42   330.1 2832.92   350.1 2838.19
   363.8 2839.96   376.8 2842.74   406.6 2851.02   418.9  2855.4   440.7 2860.03
#Mann= 4 ,-1,0
       0     .06       0      80      .1       0   154.1    .045       0
  176.39      .1       0
Bank Sta=154.1,176.39
XS Rating Curve= 0 ,0
Exp/Cntr=0.3,0.1

Type RM Length L Ch R = 1 ,7083    ,217.4,220.6,221.1
XS GIS Cut Line= 2
2425540.38373757717336.0641290242425884.37734144717545.451540075
#Sta/Elev= 30
       0 2837.33    27.9 2824.25    37.2 2820.97    50.1 2817.67    55.9 2815.23
    74.7 2801.62    85.1 2795.89    93.8 2790.18   102.5 2788.69   121.5 2787.08
   130.9  2788.2   140.2 2791.47   168.3 2793.14   196.4 2793.12   201.1 2792.28
  209.42 2789.01   215.2 2788.47   227.7 2789.02   233.9 2790.91   238.6 2794.07
     251 2807.37     262 2816.03   266.7 2818.62   271.4 2820.06     283 2829.05
   303.4 2841.21   317.9 2844.66     350  2846.6   388.4 2850.33   402.7 2852.78
#Mann= 5 ,-1,0
       0      .1       0  209.42    .045       0   227.7      .1       0
     240     .07       0     350      .1       0
#XS Ineff= 2 , 0
          169.92 2797.51
Permanent Ineff=
       F       F
Bank Sta=209.42,227.7
XS Rating Curve= 0 ,0
Exp/Cntr(USF)=0,0
Exp/Cntr=0.3,0.1

Type RM Length L Ch R = 1 ,6862    ,269.3,266.9,263.3
XS GIS Cut Line= 2
2425430.85831774717426.2980892042425730.99531774717770.466089204
#Sta/Elev= 30
       0 2850.47    17.2 2844.33    44.6 2829.84    51.6 2827.03    68.9 2813.09
    87.2 2796.98    93.3 2793.01   107.9 2793.88   115.3 2792.99   119.2 2790.23
   124.9 2784.18   127.7 2782.48   131.2  2781.1   142.12779.785   147.6 2778.49
   154.2 2778.43  166.562779.785   175.9 2783.32   190.1 2784.99   204.3 2784.83
   209.9 2786.49   216.1 2790.69   235.4 2807.92   263.7 2827.35   269.2  2828.9
   306.3 2831.34   361.1 2838.31   379.3 2838.77   408.4 2838.05   456.7 2839.69
#Mann= 5 ,-1,0
       0      .1       0   142.1    .045       0  166.56      .1       0
     320     .06       0     410      .1       0
Bank Sta=142.1,166.56
XS Rating Curve= 0 ,0
Exp/Cntr=0.3,0.1

Type RM Length L Ch R = 1 ,6595    ,272.2,271.7,271
XS GIS Cut Line= 2
2425284.46579073717681.7195377442425761.40378257718040.669385261
#Sta/Elev= 30
       0 2824.21     9.6 2811.98    14.7 2800.48    16.5 2797.48      39 2776.38
    45.7  2773.9    54.7  2773.6    59.7 2774.69   67.62 2773.98    79.4 2773.47
    98.9 2773.95     108 2774.32   119.4  2776.5   127.9 2783.26   130.8 2784.46
   165.4 2781.52   182.2 2778.42   194.9 2779.37   225.3 2787.54   251.9 2798.57
   282.2 2807.95     305 2816.91   311.7 2818.54   365.1 2825.53   420.2 2829.09
     498 2837.08   517.9 2835.23   545.3 2840.95   564.5 2843.46   596.9 2853.15
#Mann= 3 ,-1,0
       0      .1       0   67.62    .045       0    98.9      .1       0
Bank Sta=67.62,98.9
XS Rating Curve= 0 ,0
Exp/Cntr(USF)=0,0
Exp/Cntr=0.3,0.1

Type RM Length L Ch R = 1 ,6324    ,365.2,366,383.4
XS GIS Cut Line= 3
2425016.75609589717832.6670379182425417.44042699718101.415314396
2425634.03194537718201.186433676
#Sta/Elev= 30
       0 2830.43    69.1 2807.51    95.6 2800.03   124.5 2794.15   173.3 2777.09
  197.33 2764.36     202 2762.87  215.54 2764.37   242.1 2764.34   253.6 2767.01
   273.8 2767.72   288.3 2763.25   302.7 2767.88   317.2  2774.6   331.2 2776.17
   367.1 2774.51   386.3 2775.97   403.1 2775.46   423.7 2769.43   437.6 2768.11
   455.4 2769.74     467 2773.46   476.1 2778.64   511.9 2804.78   525.1 2812.91
   532.6 2816.07   544.7 2818.66   559.7 2818.33   632.1 2828.38   720.9 2852.94
#Mann= 3 ,-1,0
       0      .1       0  197.33    .045       0  215.54      .1       0
Bank Sta=197.33,215.54
XS Rating Curve= 0 ,0
Exp/Cntr=0.3,0.1

Type RM Length L Ch R = 1 ,5958    ,404.3,404.9,406.9
XS GIS Cut Line= 4
2424943.01334399718023.1224190552425090.38694165718196.201741151
 2425215.8382693718360.4649493932425372.86484068718449.389766825
#Sta/Elev= 30
       0 2767.76    20.3 2764.67    39.5 2763.67    81.5 2765.73      92 2765.22
     113 2761.79     134 2763.48   161.2 2763.14   186.6 2760.93   200.9 2762.62
   217.9 2762.25   263.2 2756.13     275 2758.57   289.2 2754.71     304 2753.38
   319.1 2753.26     332 2755.64  348.25  2753.4   366.3 2753.05   380.5 2753.39
     395 2756.66   408.2 2764.74   419.8 2769.03   429.9  2775.9   448.2  2792.3
     462  2793.5   471.2 2798.83   512.5 2808.59   544.7 2814.25   614.5 2833.54
#Mann= 3 ,-1,0
       0      .1       0  348.25    .045       0   380.5      .1       0
Bank Sta=348.25,380.5
XS Rating Curve= 0 ,0
Exp/Cntr(USF)=0,0
Exp/Cntr=0.3,0.1

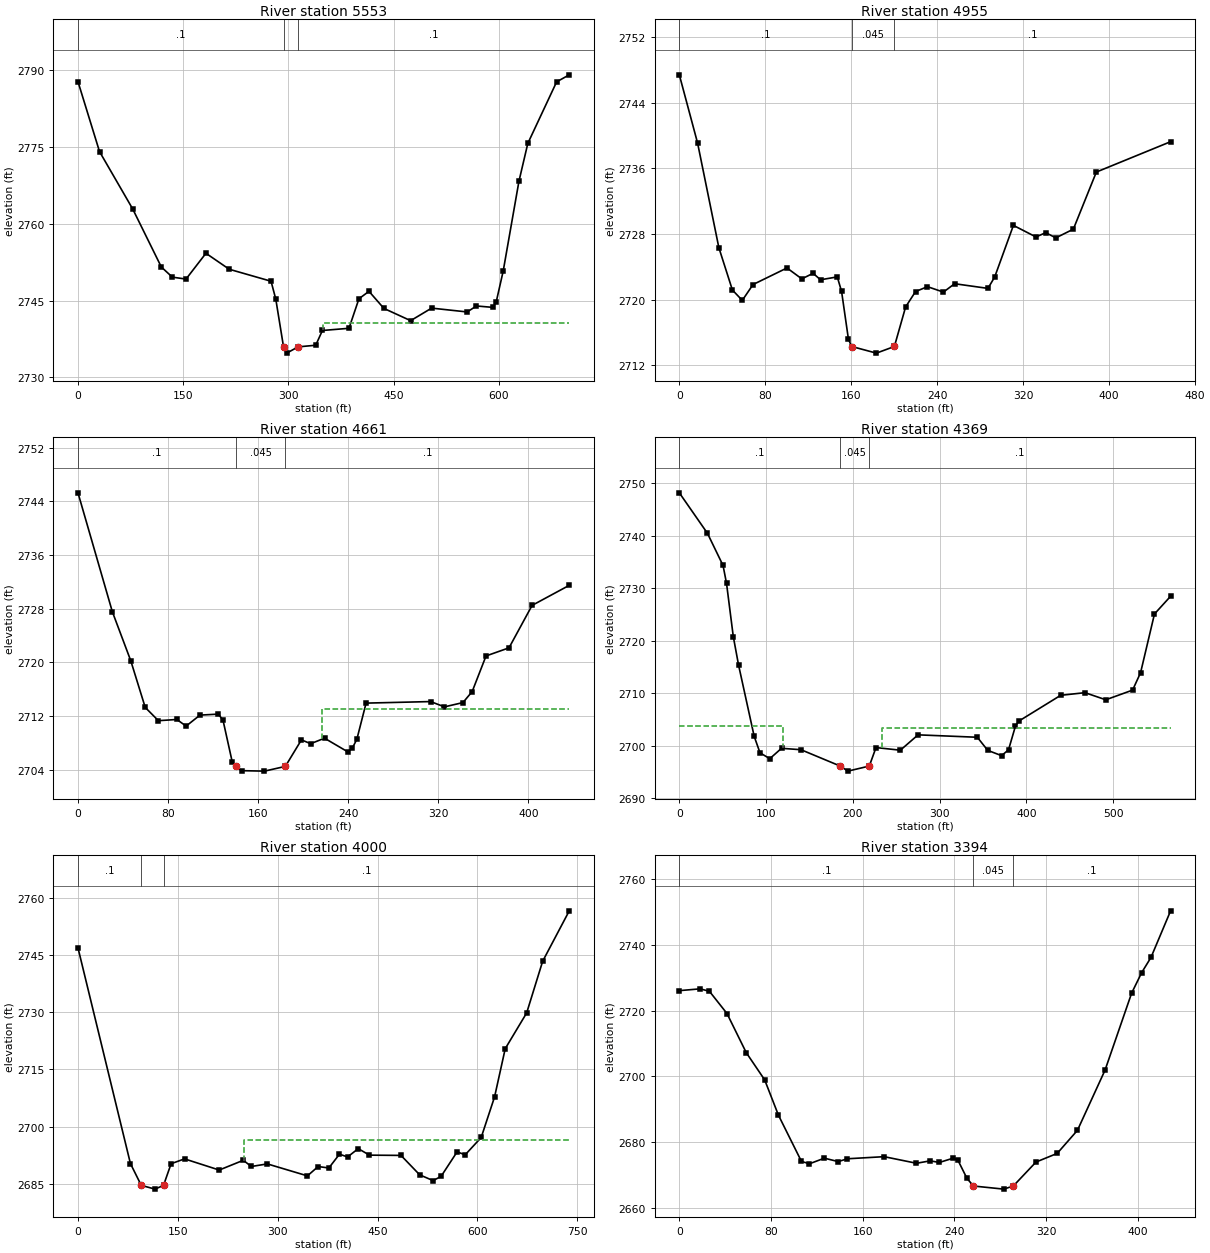
Type RM Length L Ch R = 1 ,5553    ,595.8,597.6,595.5
XS GIS Cut Line= 3
 2424664.3971993718255.2770000392424887.88583783718606.421310014
2425134.42749933718747.526363652
#Sta/Elev= 30
       0 2787.76    30.7  2774.1    78.1 2762.87   118.8 2751.56   134.5 2749.58
     154  2749.2   182.4 2754.24   215.6 2751.12   275.2 2748.78     282 2745.26
  293.052735.929   297.6 2734.74  313.65 2735.96   338.9 2736.28   348.4 2739.16
   386.3 2739.59   400.5 2745.36   414.8 2746.81   436.1 2743.47   474.2 2741.08
   504.1 2743.53   554.8 2742.78     568 2743.95   591.7 2743.67   596.3 2744.82
   606.1 2750.75   628.6 2768.32   641.2 2775.69   682.3 2787.72   700.3 2789.09
#Mann= 3 ,-1,0
       0      .1       0  293.05    .045       0  313.65      .1       0
#XS Ineff= 2 , 0
                           349.4         2740.55
Permanent Ineff=
       F       F
Bank Sta=293.05,313.65
XS Rating Curve= 0 ,0
Exp/Cntr=0.3,0.1

Type RM Length L Ch R = 1 ,4955    ,308.4,293.9,281.2
XS GIS Cut Line= 3
2424348.64003068718736.1090273242424545.45566943718973.035207643
2424684.59905966719026.938911113
#Sta/Elev= 30
       0 2747.41      17 2739.09    36.8 2726.34    49.4 2721.18    58.6 2719.92
    68.6 2721.85   100.2 2723.87     114 2722.54   124.5 2723.22   131.4 2722.43
     147 2722.78     151 2721.01   157.4 2715.17  160.452714.297   183.4 2713.49
  200.142714.299   210.6 2719.12   219.8 2720.99   230.9 2721.59   245.8 2720.93
   256.2 2721.95   287.2 2721.38   293.5 2722.77   310.9 2729.06   331.9 2727.65
     341 2728.17   350.4 2727.54   366.7  2728.6   388.1 2735.56   457.2 2739.26
#Mann= 3 ,-1,0
       0      .1       0  160.45    .045       0  200.14      .1       0
Bank Sta=160.45,200.14
XS Rating Curve= 0 ,0
Exp/Cntr(USF)=0,0
Exp/Cntr=0.3,0.1

Type RM Length L Ch R = 1 ,4661    ,287.1,291.8,296.3
XS GIS Cut Line= 2
2424162.40852907719091.8224252952424588.41741929719185.712463698
#Sta/Elev= 30
       0 2745.28    30.5 2727.56    46.9 2720.23    59.7 2713.29    71.4 2711.31
    87.8 2711.49      96  2710.5   108.3 2712.14   124.7 2712.29   128.8 2711.36
     137 2705.13  140.022704.497   145.2 2703.86   165.6 2703.79  184.122704.496
   198.4 2708.45   206.6 2707.88   218.9  2708.7   239.4 2706.68   243.5  2707.2
   247.6 2708.53   255.8 2713.93   313.1 2714.16   325.4 2713.37   341.8 2714.01
     350 2715.65   362.3 2720.96   382.7 2722.17   403.2  2728.5   436.2 2731.49
#Mann= 3 ,-1,0
       0      .1       0  140.02    .045       0  184.12      .1       0
#XS Ineff= 2 , 0
                          217.07         2713.04
Permanent Ineff=
       F       F
Bank Sta=140.02,184.12
XS Rating Curve= 0 ,0
Exp/Cntr(USF)=0,0
Exp/Cntr=0.3,0.1

Type RM Length L Ch R = 1 ,4369    ,376.7,369.4,363.9
XS GIS Cut Line= 3
2424059.38288532719312.7668839182424305.82886381719439.356621501
2424594.83054131719452.284935126
#Sta/Elev= 30
       0 2748.13    32.4 2740.44    50.4 2734.31    54.4 2730.92    62.2  2720.8
    68.3 2715.36    86.3 2701.81      93 2698.68   104.3 2697.57   117.8 2699.54
   140.3 2699.27  185.442696.166   194.3  2695.2  218.992696.165   226.7 2699.68
   254.8 2699.18   275.2  2702.1   343.5 2701.64   355.5 2699.15   371.5 2698.14
   379.5 2699.27   387.5 2703.79   391.5 2704.73   439.6 2709.62   467.6 2710.12
   491.6 2708.77   522.5 2710.61   531.7 2713.93   547.7 2725.09   566.3 2728.46
#Mann= 3 ,-1,0
       0      .1       0  185.44    .045       0  218.99      .1       0
#XS Ineff= 2 , 0
             120 2703.76  234.15         2703.31
Permanent Ineff=
       F       F
Bank Sta=185.44,218.99
XS Rating Curve= 0 ,0
Exp/Cntr(USF)=0,0
Exp/Cntr=0.3,0.1

Type RM Length L Ch R = 1 ,4000    ,607.8,606.3,608.6
XS GIS Cut Line= 2
2423892.79617746  719659.00328322424627.95934497719724.722210796
#Sta/Elev= 30
       0 2746.92    78.8  2690.3   95.042684.584   115.8 2683.59  128.542684.583
   139.9 2690.26   160.1 2691.53   212.2  2688.6   248.4 2691.16   260.4 2689.53
   284.5 2690.21   344.7 2687.07   360.8 2689.52   376.9 2689.14   392.9 2692.77
     405 2692.03   421.1 2694.22   437.9 2692.51   485.3 2692.44   513.4 2687.34
   533.5 2685.83   545.5 2686.93   569.6 2693.38   581.7 2692.59   605.8 2697.15
   625.9 2707.81   641.9 2720.46   674.1 2729.84   698.1 2743.39   738.1 2756.64
#Mann= 3 ,-1,0
       0      .1       0   95.04    .045       0  128.54      .1       0
#XS Ineff= 2 , 0
                          249.76         2696.55
Permanent Ineff=
       F       F
Bank Sta=95.04,128.54
XS Rating Curve= 0 ,0
Exp/Cntr(USF)=0,0
Exp/Cntr=0.3,0.1

Type RM Length L Ch R = 1 ,3394    ,403.1,409.4,418.3
XS GIS Cut Line= 2
2424057.99364889720114.3566556352424485.15835918  720151.2898928
#Sta/Elev= 30
       0 2726.11    18.2 2726.66    26.3  2725.9    41.6 2719.14    58.4 2707.23
    74.5 2698.92    86.5 2688.17   106.6 2674.07   113.6 2673.36   126.6 2675.06
   138.7 2674.02   146.7 2674.88   178.8 2675.52     207 2673.51     219 2674.25
     227 2673.76   239.1 2675.07   243.1 2674.48   251.1 2668.88  256.762666.578
   283.2 2665.63   291.52666.579   311.3 2673.88   329.8 2676.51   347.5 2683.56
   371.6 2701.91   394.8 2725.37   403.6 2731.63   411.7 2736.25   428.8 2750.43
#Mann= 3 ,-1,0
       0      .1       0  256.76    .045       0   291.5      .1       0
Bank Sta=256.76,291.5
XS Rating Curve= 0 ,0
Exp/Cntr(USF)=0,0
Exp/Cntr=0.3,0.1

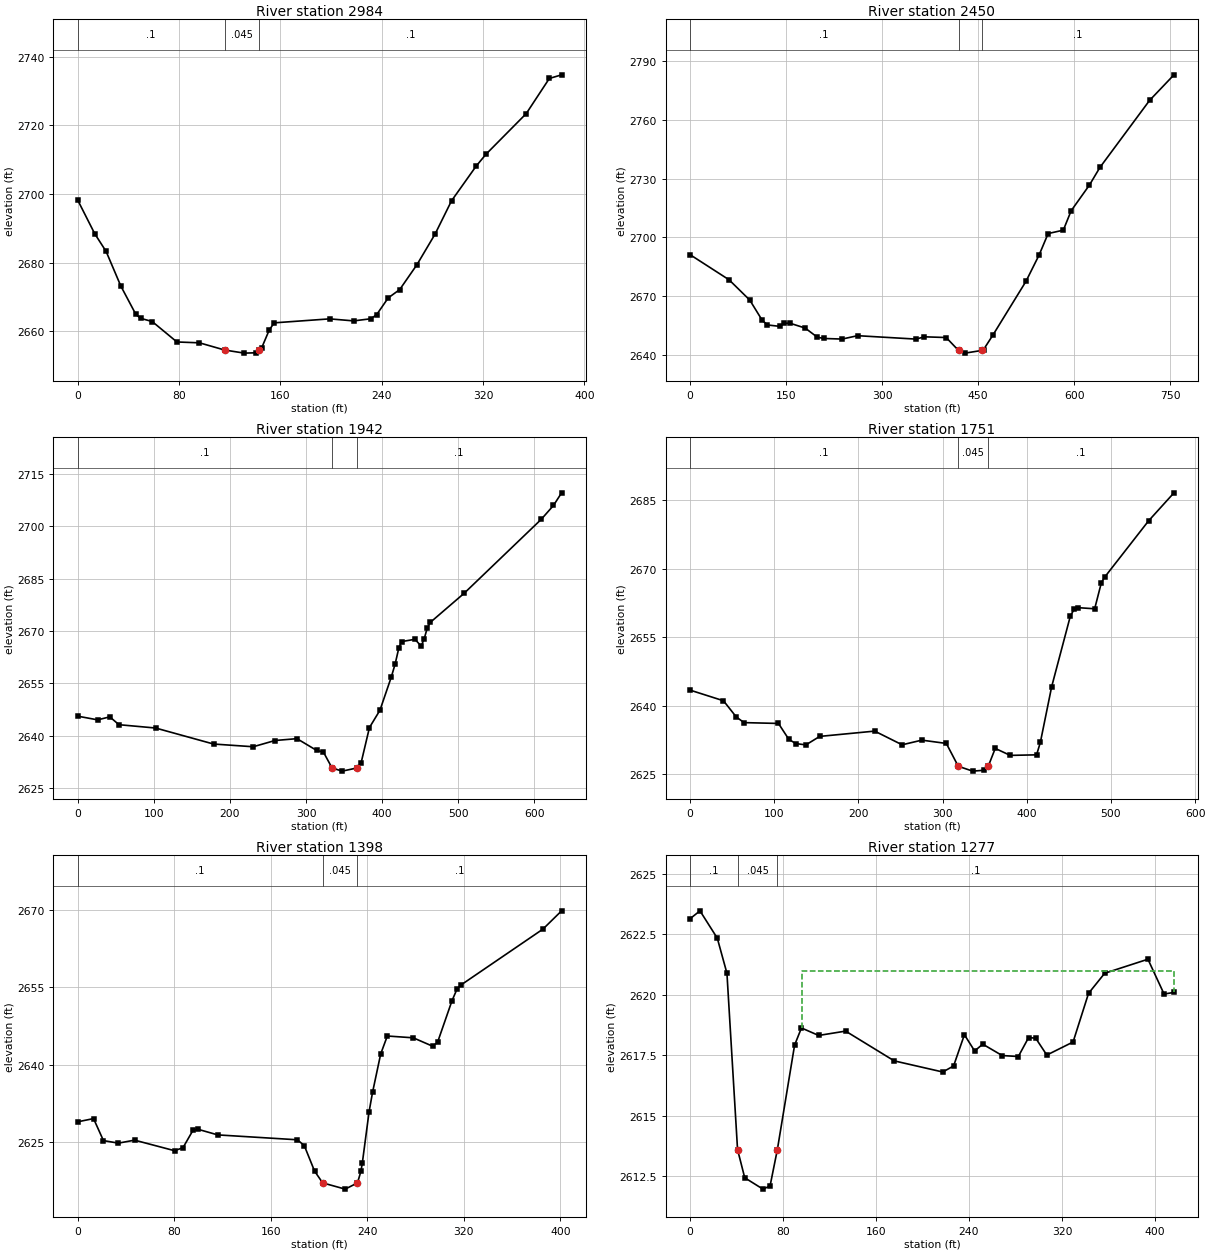
Type RM Length L Ch R = 1 ,2984    ,534.4,534.7,540.9
XS GIS Cut Line= 2
2423996.32561209720418.7724515482424332.70190863720599.991652176
#Sta/Elev= 30
       0 2698.28    13.5 2688.45    22.5 2683.28    34.1 2673.21      46 2664.93
    49.8 2663.79    58.9 2662.86    78.4 2656.91    96.2 2656.66  116.032654.566
   131.6 2653.66   140.7 2653.76  143.572654.566   145.2  2655.1   151.3 2660.41
   155.2 2662.48     199 2663.64   217.9 2663.05   231.5 2663.67   236.1 2664.88
   245.2 2669.74   254.3 2672.18   267.9 2679.42   282.2 2688.33   295.2 2698.03
   314.7 2708.16   322.4 2711.59   354.2 2723.44   372.4 2733.66   382.1 2734.72
#Mann= 3 ,-1,0
       0      .1       0  116.03    .045       0  143.57      .1       0
Bank Sta=116.03,143.57
XS Rating Curve= 0 ,0
Exp/Cntr(USF)=0,0
Exp/Cntr=0.3,0.1

Type RM Length L Ch R = 1 ,2450    ,506.7,507.5,508.2
XS GIS Cut Line= 3
2423650.44184974720755.3061373312424131.95287514721076.222502149
2424305.54592251721111.483589895
#Sta/Elev= 30
       0 2691.26    61.1 2678.41    93.4 2668.07   112.6 2657.88   120.9  2655.4
   140.4 2654.68   146.8  2656.2   155.9 2656.31   179.9 2653.82   198.7 2649.19
   208.8 2648.51   237.6 2648.21   261.7 2649.93     353 2648.19     366 2649.36
   400.1 2648.99  419.342642.411   429.5 2641.04   455.82642.412   458.4 2642.83
   473.2 2650.32   524.7 2677.64   545.3 2691.14   559.3    2702     583 2703.72
   595.2  2713.6   623.8 2726.72   640.1 2735.67   717.7 2769.87   755.8 2782.91
#Mann= 3 ,-1,0
       0      .1       0  419.34    .045       0   455.8      .1       0
Bank Sta=419.34,455.8
XS Rating Curve= 0 ,0
Exp/Cntr(USF)=0,0
Exp/Cntr=0.3,0.1

Type RM Length L Ch R = 1 ,1942    ,194,191.1,188.3
XS GIS Cut Line= 4
 2423644.7615801721082.9266953372423660.98344874721366.569883452
2423776.58987572721451.1806911692423982.73161947721481.016996186
#Sta/Elev= 30
       0 2645.59    26.3 2644.53    42.3 2645.39    54.3 2643.14   102.4 2642.19
   178.5  2637.6   230.6 2636.82   259.3 2638.61   288.1 2639.14     314 2635.76
   322.8 2635.31  334.222630.721   347.5 2629.83  366.662630.721   372.3 2632.16
   383.3 2642.32   397.1 2647.29     412  2656.8   417.1 2660.58   421.9 2665.16
   425.6 2666.97   443.1 2667.63   451.2 2665.67   455.2 2667.76   459.3  2670.9
   463.3 2672.49   507.8 2680.84   608.9 2702.01     625 2705.99   635.7 2709.62
#Mann= 3 ,-1,0
       0      .1       0  334.22    .045       0  366.66      .1       0
Bank Sta=334.22,366.66
XS Rating Curve= 0 ,0
Exp/Cntr(USF)=0,0
Exp/Cntr=0.3,0.1

Type RM Length L Ch R = 1 ,1751    ,346,352.9,350.9
XS GIS Cut Line= 4
2423526.35826817721258.2189048782423586.73381933721555.000280662
 2423726.2438289721624.5037669482423842.26855456721629.364440548
#Sta/Elev= 30
       0 2643.41    39.8 2641.07    54.9 2637.54    64.2 2636.28   105.1  2636.1
   117.3 2632.65   125.5 2631.69   137.7  2631.4   154.1 2633.26   219.4 2634.42
     252 2631.42   275.4 2632.44   304.5 2631.72  318.652626.718   335.8 2625.65
   349.2 2625.84  354.312626.719   362.6 2630.63   380.4  2629.1   411.7 2629.22
   416.2 2631.96   429.6 2644.14   451.9 2659.69   456.4 2661.12   461.2 2661.47
   480.7 2661.23   488.7 2666.98   492.7 2668.19   544.7 2680.49   574.9 2686.64
#Mann= 3 ,-1,0
       0      .1       0  318.65    .045       0  354.31      .1       0
Bank Sta=318.65,354.31
XS Rating Curve= 0 ,0
Exp/Cntr(USF)=0,0
Exp/Cntr=0.3,0.1

Type RM Length L Ch R = 1 ,1398    ,124.7,121.3,120.7
XS GIS Cut Line= 4
2423540.13393328721708.3304513972423581.22076188721879.330013293
2423644.12555325721938.1555997362423782.65510922721926.947597321
#Sta/Elev= 30
       0 2628.88    13.2 2629.51    21.4 2625.23    33.8 2624.74    47.2 2625.32
    80.3 2623.27    87.3 2623.85    95.5  2627.2    99.6 2627.44   116.1 2626.34
   182.1 2625.39   187.8 2624.26   196.3 2619.31  203.022617.016   221.7  2615.8
  231.872617.015   234.7 2619.24   235.9  2620.9   241.5 2630.87   244.4 2634.66
   251.1 2642.07   256.6 2645.56   278.1 2645.21   294.1 2643.58   298.2 2644.32
   310.2 2652.43   314.2  2654.6   317.7 2655.49   385.5 2666.33     401 2669.89
#Mann= 3 ,-1,0
       0      .1       0  203.02    .045       0  231.87      .1       0
Bank Sta=203.02,231.87
XS Rating Curve= 0 ,0
Exp/Cntr(USF)=0,0
Exp/Cntr=0.3,0.1

Type RM Length L Ch R = 1 ,1277    ,44.4,44.1,42
XS GIS Cut Line= 2
2423532.79925306721993.2682407612423891.49579439722204.728931471
#Sta/Elev= 30
       0 2623.14     8.6 2623.47    23.5 2622.34    31.8 2620.89   40.932613.604
    47.1 2612.44    62.8 2611.97    68.9  2612.1   75.182613.604      90 2617.92
    95.9 2618.63   110.7 2618.32   133.9  2618.5   175.7 2617.27   217.5 2616.81
   226.8 2617.06   236.1 2618.35   244.9 2617.68   251.9 2617.96   268.6 2617.49
   282.5 2617.45   291.3 2618.23   297.4 2618.21     307 2617.51   329.6 2618.05
   342.9 2620.06   356.8 2620.89     394 2621.47   407.9 2620.03   416.4  2620.1
#Mann= 3 ,-1,0
       0      .1       0   40.93    .045       0   75.18      .1       0
#XS Ineff= 2 , 0
                           96.75         2620.98
Permanent Ineff=
       F       F
Bank Sta=40.93,75.18
XS Rating Curve= 0 ,0
Exp/Cntr(USF)=0,0
Exp/Cntr=0.3,0.1

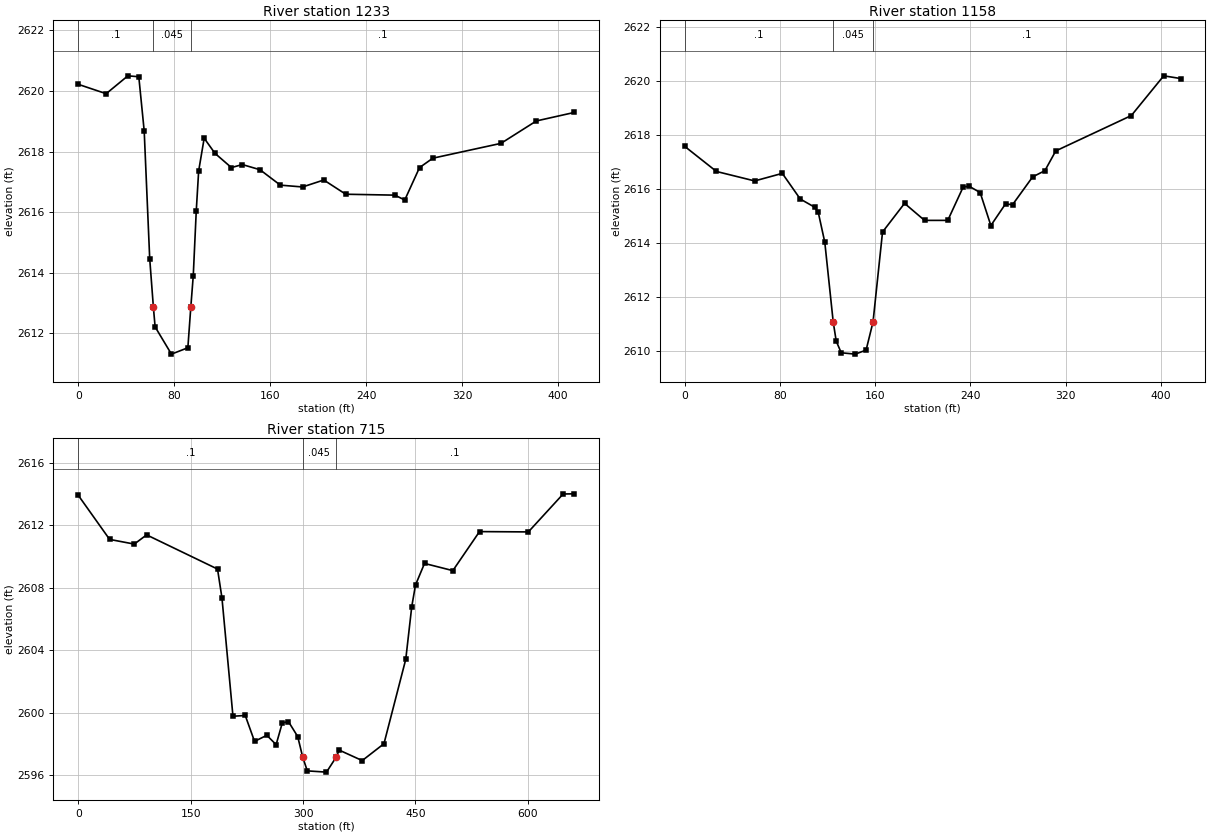
Type RM Length L Ch R = 1 ,1233    ,66.7,74.2,80.5
XS GIS Cut Line= 2
2423507.67334931722028.4965965192423871.99553836722223.908829311
#Sta/Elev= 30
       0 2620.22    23.3 2619.91    41.4  2620.5    50.5 2620.47      55 2618.68
    59.6 2614.46   62.682612.851    64.1 2612.21    77.7 2611.31    91.4 2611.52
   93.832612.852    95.9  2613.9    98.4 2616.04   100.4 2617.36     105 2618.44
     114 2617.94   127.7 2617.47   136.8 2617.57   151.5  2617.4   168.5 2616.89
     187 2616.83   204.7 2617.06     223 2616.59   263.9 2616.56   272.2  2616.4
   284.5 2617.47   295.6 2617.78   352.4 2618.27   381.9 2619.01   413.4 2619.29
#Mann= 3 ,-1,0
       0      .1       0   62.68    .045       0   93.83      .1       0
Bank Sta=62.68,93.83
XS Rating Curve= 0 ,0
Exp/Cntr(USF)=0,0
Exp/Cntr=0.3,0.1

Type RM Length L Ch R = 1 ,1158    ,459.6,443.5,429.5
XS GIS Cut Line= 3
2423464.59700635 722019.888265282423568.13176497722156.029546689
2423784.74777289722271.736004635
#Sta/Elev= 30
       0 2617.57    26.7 2616.64    58.8 2616.29      82 2616.57    97.1 2615.62
   109.1 2615.32   112.2 2615.13   117.7 2614.02  124.772611.071   127.3 2610.36
   131.5 2609.93   143.3 2609.88   152.4 2610.03  158.222611.071   166.2  2614.4
   184.7 2615.46   201.5 2614.83     221 2614.83     234 2616.07   239.1 2616.09
   248.2 2615.86   257.2 2614.64   269.5 2615.44   275.4 2615.41   292.3 2616.44
   302.6 2616.67   311.7  2617.4   375.2 2618.71   402.4 2620.18   416.6 2620.08
#Mann= 3 ,-1,0
       0      .1       0  124.77    .045       0  158.22      .1       0
Bank Sta=124.77,158.22
XS Rating Curve= 0 ,0
Exp/Cntr(USF)=0,0
Exp/Cntr=0.3,0.1

Type RM Length L Ch R = 1 ,715     ,,,
XS GIS Cut Line= 4
2423203.33909325721924.4326551262423134.28271902722211.399587547
2423267.43398633722260.5325680592423488.28944865722302.245541771
#Sta/Elev= 30
       0 2613.93    41.9  2611.1    74.8  2610.8    91.3 2611.39   185.9  2609.2
   191.8 2607.36   206.5 2599.77   222.9 2599.82   235.3 2598.16   251.7 2598.55
   264.1 2597.95   272.3 2599.34   280.5 2599.43   292.9 2598.47  299.58 2597.15
   305.7 2596.27   331.3 2596.19   344.1 2597.14   348.3  2597.6     379 2596.93
     408 2598.01   437.1 2603.42   445.1  2606.8   450.1 2608.18   462.1 2609.56
   499.9  2609.1   535.5  2611.6   600.7 2611.58   647.1 2614.01   661.8 2614.02
#Mann= 3 ,-1,0
       0      .1       0  299.58    .045       0   344.1      .1       0
Bank Sta=299.58,344.1
XS Rating Curve= 0 ,0
Exp/Cntr(USF)=0,0
Exp/Cntr=0.3,0.1
LCMann Table=0

Chan Stop Cuts=-1
Use User Specified Reach Order=0
Composite Channel Slope=5